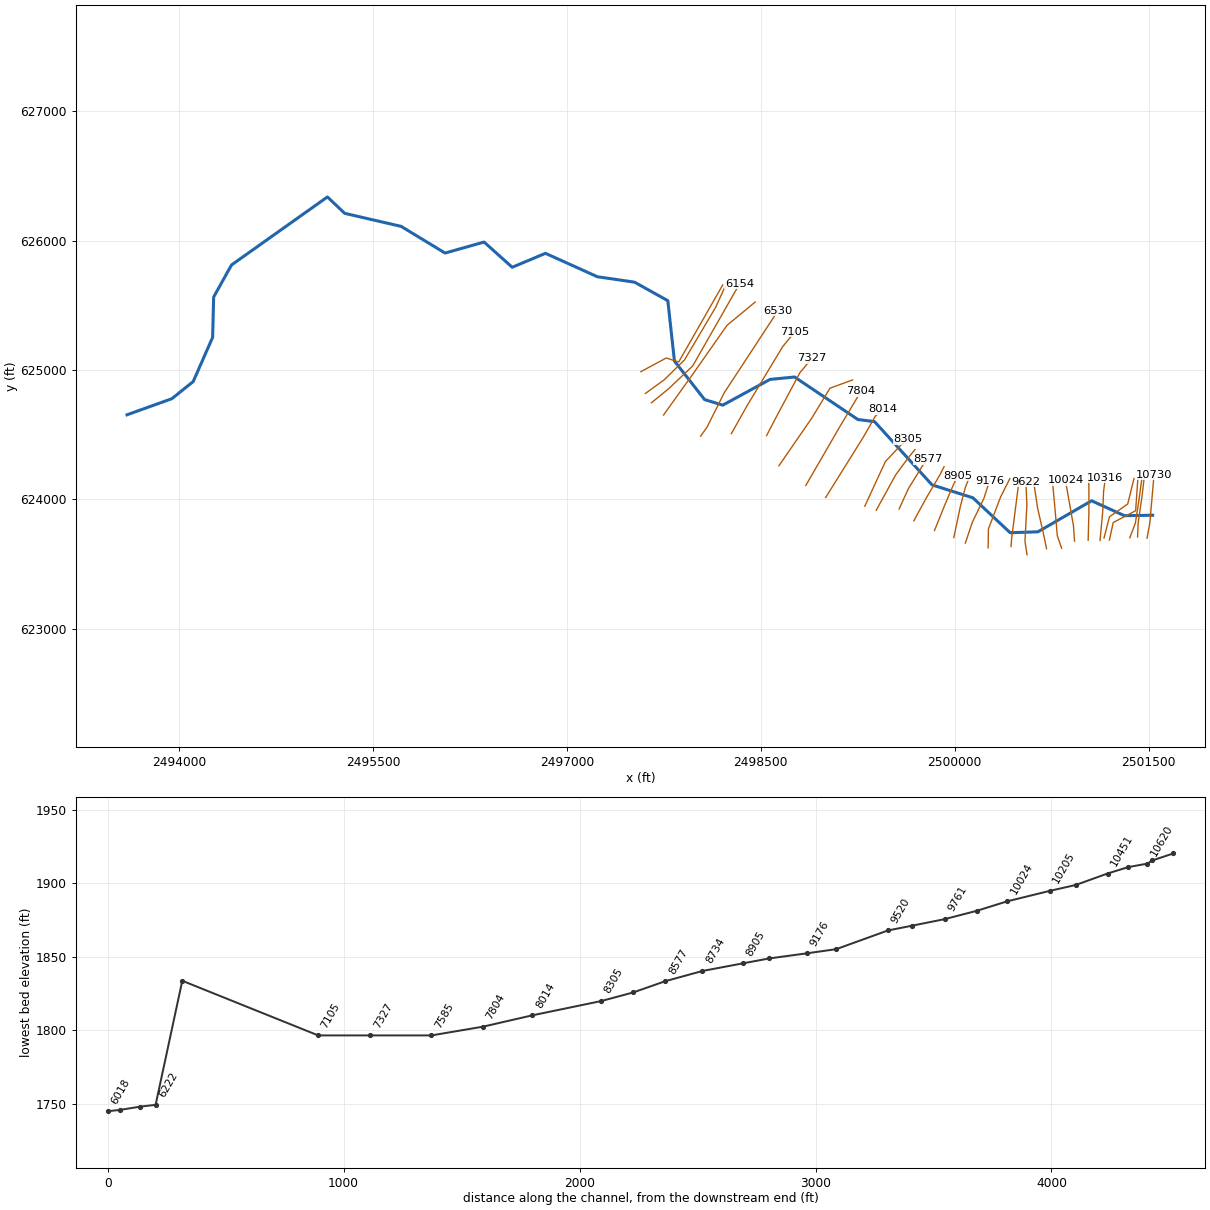
--- LROUGHRN.prj (project) ---

Proj Title=LROUGHRN
Current Plan=p01
Default Exp/Contr=0,0
English Units
Geom File=g01
Flow File=f01
Plan File=p01
Background Map Layer=QC
BEGIN DESCRIPTION:
Stream Name: Little Rough Run
Flood Zone: Zone A
Pendleton County, WV
WVDHSEM Flood Warning & Analysis Mapping
HEC-RAS Version: 5.0.7
Hydrology Method:
Regression was used
Model Notes:
Model ties in with Rough Run
END DESCRIPTION:
DSS Export Rating Curves= 0
DSS Export Rating Curve Sorted= 0
DSS Export Volume Flow Curves= 0
DXF OffsetX= 0
DXF OffsetY= 0
DXF ScaleX= 0
DXF ScaleY= 0

--- LROUGHRN.p01 (plan) ---

Plan Title=Floodplain
Program Version=5.07
Short Identifier=Floodplain
Geom File=g01
Flow File=f01
Subcritical Flow
K Sum by GR= 0
Std Step Tol= 0.01
Critical Tol= 0.01
Num of Std Step Trials= 20
Max Error Tol= 0.3
Flow Tol Ratio= 0.001
Split Flow NTrial= 30
Split Flow Tol= 0.02
Split Flow Ratio= 0.02
Log Output Level= 0
Friction Slope Method= 1
Unsteady Friction Slope Method= 2
Unsteady Bridges Friction Slope Method= 1
Parabolic Critical Depth
Global Vel Dist= 0 , 0 , 0
Global Log Level= 0
CheckData=True
Encroach Param=-1 ,0,0, 0
Mapping Interval=1HOUR
Computation Time Step Use Courant=        0
Computation Time Step Use Time Series=    0
Computation Time Step Count To Double=0
Computation Time Step Max Doubling=0
Computation Time Step Max Halving=0
Computation Time Step Residence Courant=0
Run HTab= 0
Run UNet= 0
Run Sediment= 0
Run PostProcess= 0
Run WQNet= 0
Run RASMapper= 0
UNET Theta= 0
UNET Theta Warmup= 0
UNET ZTol= 0
UNET ZSATol= 0
UNET MxIter= 0
UNET Max Iter WO Improvement= 0
UNET MaxInSteps= 0
UNET DtIC= 0
UNET DtMin= 0
UNET MaxCRTS= 0
UNET WFStab= 0
UNET SFStab= 0
UNET WFX= 1
UNET SFX= 1
UNET 1D Methodology=Finite Difference
UNET DSS MLevel= 1
UNET Pardiso=0
UNET DZMax Abort= 0
UNET Use Existing IB Tables= 0
UNET Froude Reduction=False
UNET Froude Limit= 0
UNET Froude Power= 0
UNET D1 Cores= 0
UNET D2 Coriolis=0
UNET D2 Cores= 0
UNET D2 Theta= 1
UNET D2 Theta Warmup= 1
UNET D2 Z Tol= 0.01
UNET D2 Volume Tol= 0.01
UNET D2 Max Iterations= 20
UNET D2 Equation= 0
UNET D2 RampUpFraction=0.1
UNET D2 TimeSlices= 1
UNET D2 BCVolumeCheck=0
UNET D1D2 MaxIter= 0
UNET D1D2 ZTol=0.01
UNET D1D2 QTol=0.1
UNET D1D2 MinQTol=1
Write IC File= 0
Write IC File at Fixed DateTime=0
Write IC File at Sim End=0
Echo Input=False
Echo Parameters=False
Echo Output=False
Write Detailed= 0
HDF Write Warmup=0
HDF Write Time Slices=0
HDF Flush=0
HDF Face Node Velocities=0
HDF Compression= 1
HDF Chunk Size= 1
HDF Spatial Parts= 1
HDF Use Max Rows=0
HDF Fixed Rows= 1
Calibration Method= 0
Calibration Iterations= 20
Calibration Max Change=0.05
Calibration Tolerance=0.2
Calibration Maximum=1.5
Calibration Minimum=0.5
Calibration Optimization Method= 1
WQ AD Non Conservative
WQ ULTIMATE=-1
WQ Max Comp Step=1HOUR
WQ Output Interval=15MIN
WQ Output Selected Increments= 0
WQ Output face flow=0
WQ Output face velocity=0
WQ Output face area=0
WQ Output face dispersion=0
WQ Output cell volume=0
WQ Output cell surface area=0
WQ Output cell continuity=0
WQ Output cumulative cell continuity=0
WQ Output face conc=0
WQ Output face dconc_dx=0
WQ Output face courant=0
WQ Output face peclet=0
WQ Output face adv mass=0
WQ Output face disp mass=0
WQ Output cell mass=0
WQ Output cell source sink temp=0
WQ Output nsm pathways=0
WQ Output nsm derived pathways=0
WQ Output MaxMinRange=-1
WQ Daily Max Min Mean=-1
WQ Daily Range=0
WQ Daily Time=0
WQ Create Restart=0
WQ Fixed Restart=0
WQ System Summary=0
WQ Write To DSS=0
WQ Use Fixed Temperature=0
Sorting and Armoring Iterations= 10
XS Update Threshold= 0.02
Bed Roughness Predictor= 0
Hydraulics Update Threshold= 0.02
Energy Slope Method= 1
Volume Change Method= 1
Sediment Retention Method= 0
XS Weighting Method= 0
Number of US Weighted Cross Sections= 1
Number of DS Weighted Cross Sections= 1
Upstream XS Weight=0
Main XS Weight=1
Downstream XS Weight=0
Number of DS XS's Weighted with US Boundary= 1
Upstream Boundary Weight= 1
Weight of XSs Associated with US Boundary= 0
Number of US XS's Weighted with DS Boundary= 1
Downstream Boundary Weight= 0.5
Weight of XSs Associated with DS Boundary= 0.5
Percentile Method= 0
Sediment Output Level= 3
Mass or Volume Output= 0
Output Increment Type= 1
Profile and TS Output Increment= 1
XS Output Flag= 0
XS Output Increment= 10
Write Gradation File= 0
Read Gradation Hotstart= 0
Write HDF5 File= 1
Write Binary Output= 1
Write DSS Sediment File= 0
SV Curve= 0
Specific Gage Flag= 0

--- LROUGHRN.f01 (steady flow) ---

Flow Title=Flows
Program Version=5.07
Number of Profiles= 6
Profile Names=P100yr,P10yr,P25yr,P50yr,P500yr,P101yr
River Rch & RM=LROUGHRN,Main            ,10730
     648     303     428     535     951     789
River Rch & RM=LROUGHRN,Main            ,7585
     728     340     481     601    1070     887
River Rch & RM=LROUGHRN,Main            ,1484
     944     438     621     778    1390    1149
Boundary for River Rch & Prof#=LROUGHRN,Main            , 1
Up Type= 0
Dn Type= 3
Dn Slope=0.0093
Boundary for River Rch & Prof#=LROUGHRN,Main            , 2
Up Type= 0
Dn Type= 3
Dn Slope=0.0093
Boundary for River Rch & Prof#=LROUGHRN,Main            , 3
Up Type= 0
Dn Type= 3
Dn Slope=0.0093
Boundary for River Rch & Prof#=LROUGHRN,Main            , 4
Up Type= 0
Dn Type= 3
Dn Slope=0.0093
Boundary for River Rch & Prof#=LROUGHRN,Main            , 5
Up Type= 0
Dn Type= 3
Dn Slope=0.0093
Boundary for River Rch & Prof#=LROUGHRN,Main            , 6
Up Type= 0
Dn Type= 3
Dn Slope=0.0093
DSS Import GetInterval= 0
DSS Import GetPeak= 0
DSS Import FillOption= 0

--- LROUGHRN.g01 (geometry) ---

Geom Title=Geometry
Program Version=5.07

River Reach=LROUGHRN        ,Main
Reach XY= 30
     2501531.589      623876.851        2501313.       623873.34
      2501059.31      623988.603     2500644.093      623748.619
     2500429.615      623741.356     2500140.819      624011.651
     2499824.712      624111.731     2499380.718      624600.674
     2499251.194      624617.298     2498761.994      624945.966
2498571.72525846624927.4830642232498206.14022149624728.262689153
2498065.68170707624771.5051793152497832.46248729625069.191075486
     2497781.221      625536.254     2497524.366      625679.435
     2497236.185      625721.711     2496834.754      625902.585
     2496577.401      625794.907     2496360.161        625989.8
     2496058.002      625904.853      2495718.15      626111.326
     2495282.211      626211.734     2495148.172      626338.732
     2494406.383       625812.63      2494268.08      625564.198
     2494260.295      625252.609     2494110.005      624910.902
     2493944.971      624778.267     2493598.039      624653.741

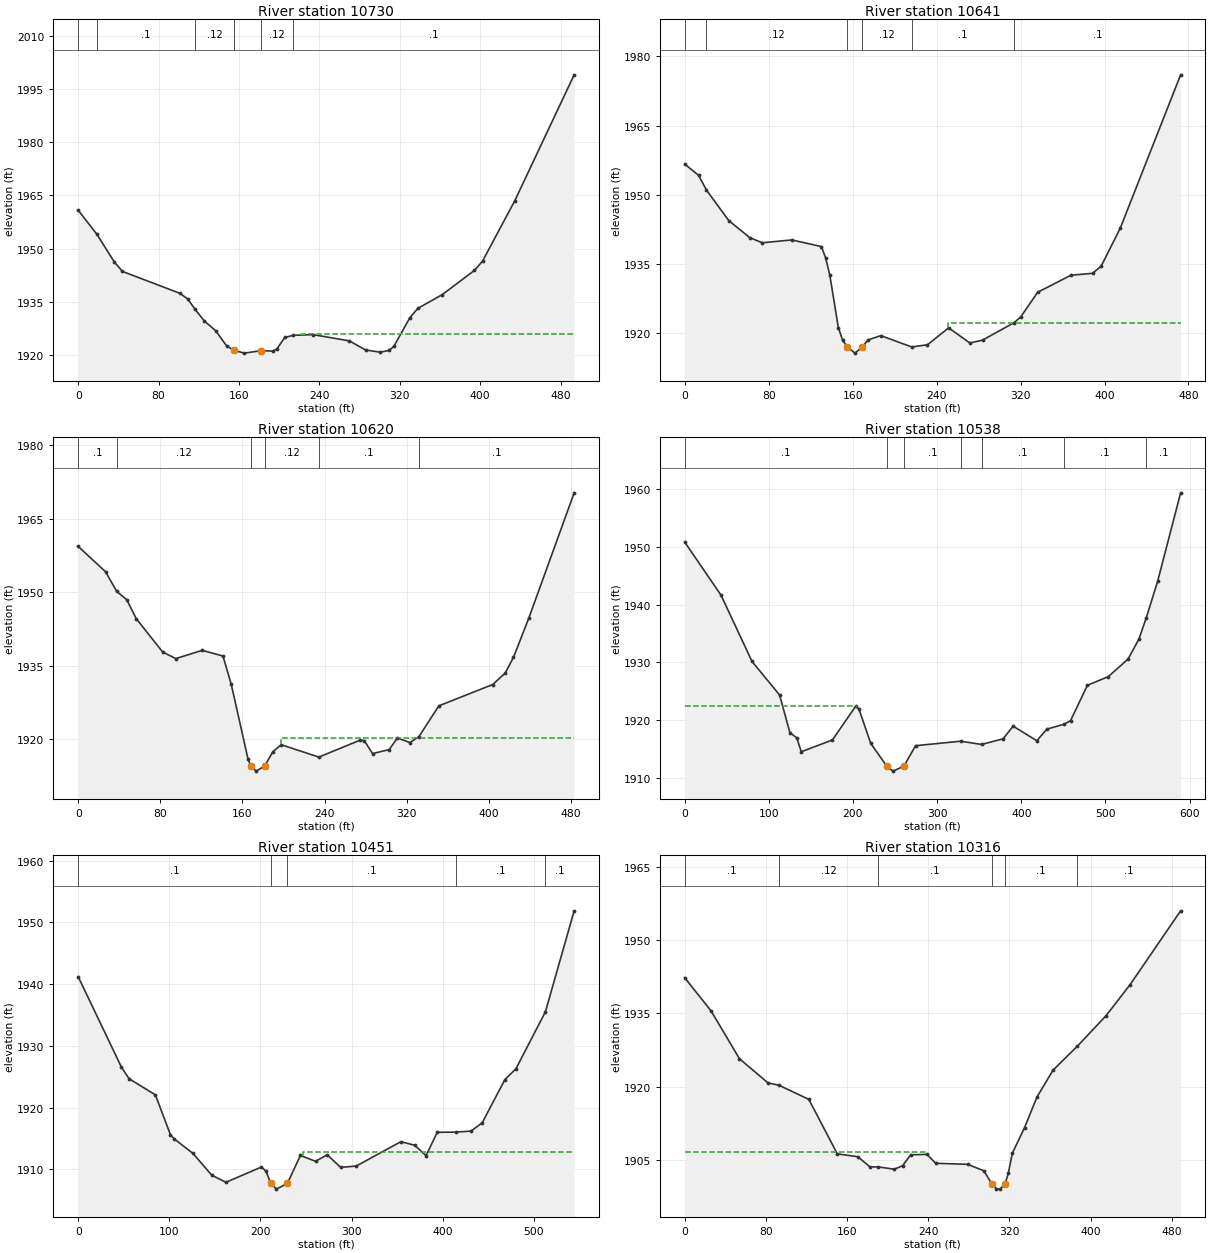
Type RM Length L Ch R = 1 ,10730   ,89.2,89.2,89.2
XS GIS Cut Line= 4
2501487.95253319623699.6790207342501509.96426027623817.847239784
2501529.65896344624047.2326061772501542.40259491624189.729576208
#Sta/Elev= 30
       0 1960.84   18.611954.022    35.8 1946.26      44 1943.54   101.2 1937.35
   109.1 1935.72  116.191932.856   125.6  1929.5   136.7 1926.82   147.8 1922.45
  155.261921.223   165.4 1920.45     182 1921.15   193.5 1921.03   197.5 1921.58
   205.6 1924.89  213.941925.481   233.7 1925.68   269.8 1923.91   285.9 1921.34
   300.6 1920.72   309.3 1921.22     314 1922.33     330 1930.45     338  1933.1
   362.2 1936.97   394.3 1943.83   402.3 1946.44   434.4 1963.49   493.5 1999.09
#Mann= 6 ,-1 , 0
       0     .12       0   18.61      .1       0  116.19     .12       0
  155.26    .045       0     182     .12       0  213.94      .1       0
#XS Ineff= 2 , 0
                          221.54         1925.76
Permanent Ineff=
       F       F
Bank Sta=155.26,182
XS Rating Curve= 0 ,0
Exp/Cntr(USF)=0,0
Exp/Cntr=0.3,0.1

Type RM Length L Ch R = 1 ,10641   ,20.9,20.9,20.9
XS GIS Cut Line= 4
2501414.96628025623708.9471163452501419.60032805623817.847239784
2501450.88015074624035.6474866622501467.09931806624178.144456693
#Sta/Elev= 30
       0 1956.66    13.2 1954.22   20.771951.019      42 1944.41      62 1940.71
      74 1939.59     102 1940.21   130.3 1938.77   134.3 1936.32   138.3 1932.55
   146.4  1921.2   150.5 1918.45   154.9 1917.03   162.2 1915.67   169.2 1916.97
   174.7 1918.53   186.8 1919.46  216.391917.008   231.3 1917.48   251.5 1921.15
   271.7 1917.87   283.8 1918.49  313.931922.287   320.2 1923.53   336.3 1928.86
     368 1932.56   388.7 1932.97   396.9 1934.57     415 1942.76   472.5    1976
#Mann= 6 ,-1 , 0
       0      .1       0   20.77     .12       0   154.9    .045       0
   169.2     .12       0  216.39      .1       0  313.93      .1       0
#XS Ineff= 2 , 0
                          251.03         1922.14
Permanent Ineff=
       F       F
Bank Sta=154.9,169.2
XS Rating Curve= 0 ,0
Exp/Cntr(USF)=0,0
Exp/Cntr=0.3,0.1

Type RM Length L Ch R = 1 ,10620   ,81.4,81.4,81.4
XS GIS Cut Line= 4
2501354.72365877623701.9960446372501397.58860097623815.530215881
2501423.07586391623976.5633771362501449.72163879624173.510408887
#Sta/Elev= 30
       0 1959.32    26.6 1954.17   37.551950.143    47.3 1948.46    56.5  1944.6
    82.2 1937.82      95 1936.45   120.7 1938.13     141 1936.98   149.1 1931.19
   165.3 1916.08     1681914.561   173.4 1913.51  181.611914.561   189.6 1917.44
   197.7  1918.9  234.41 1916.37   274.6 1919.83   278.7 1919.72   286.7 1917.08
   302.9 1917.91     311 1920.27   323.1 1919.33  331.951920.564   351.3 1926.82
   403.8 1931.17   415.9 1933.49     424  1936.7   439.1  1944.8   483.1 1970.25
#Mann= 6 ,-1 , 0
       0      .1       0   37.55     .12       0     168    .045       0
  181.61     .12       0  234.41      .1       0  331.95      .1       0
#XS Ineff= 2 , 0
                          197.53         1920.33
Permanent Ineff=
       F       F
Bank Sta=168,181.61
XS Rating Curve= 0 ,0
Exp/Cntr(USF)=0,0
Exp/Cntr=0.5,0.3

Type RM Length L Ch R = 1 ,10538   ,87.7,87.7,87.7
XS GIS Cut Line= 4
2501197.16603337623684.6183653642501226.12883215623820.164263687
2501399.90562488623911.6867078542501417.28330415624165.400825227
#Sta/Elev= 30
       0 1950.87    43.2 1941.65      80 1930.16   112.8 1924.34     125 1917.83
   133.2 1916.89   138.6  1914.5   175.5 1916.54   203.3 1922.41   207.1  1921.9
     221 1915.97  240.181911.995   247.5 1911.14  260.491911.995   274.3 1915.55
  327.99 1916.33  352.751915.769   378.3 1916.74   390.3 1918.94   418.4 1916.41
   430.4 1918.42  450.651919.274   458.5 1919.89   478.5 1926.02   503.3 1927.52
   526.7 1930.55   539.6 1933.98  548.541937.736   562.1 1944.12   589.3  1959.4
#Mann= 7 ,-1 , 0
       0      .1       0  240.18    .045       0  260.49      .1       0
  327.99     .12       0  352.75      .1       0  450.65      .1       0
  548.54      .1       0
#XS Ineff= 2 , 0
          204.94 1922.45     280         1911.53
Permanent Ineff=
       F       F
Bank Sta=240.18,260.49
XS Rating Curve= 0 ,0
Exp/Cntr(USF)=0,0
Exp/Cntr=0.5,0.3

Type RM Length L Ch R = 1 ,10451   ,134.4,134.4,134.4
XS GIS Cut Line= 4
2501155.45960311623700.8375326852501197.16603337623864.187717843
2501338.50449145 623963.819745672501387.16199341624160.766777421
#Sta/Elev= 30
       0  1941.2    47.5 1926.53    55.8 1924.68    84.7 1922.06   101.2 1915.62
   105.3 1914.94     126 1912.56   146.6 1909.04   162.2 1907.89   201.1 1910.36
   206.1 1909.71  211.351907.715   217.6 1906.78  229.661907.714   243.9 1912.24
   260.6 1911.29   273.3 1912.35     288 1910.31   305.2 1910.52   354.2 1914.47
   369.4 1913.89   381.8 1912.21   394.1 1915.99  414.921916.021   431.2 1916.19
   443.4 1917.52   468.3 1924.51   480.6 1926.32  512.831935.513   544.4 1951.89
#Mann= 5 ,-1 , 0
       0      .1       0  211.35    .045       0  229.66      .1       0
  414.92      .1       0  512.83      .1       0
#XS Ineff= 2 , 0
                          246.91         1912.84
Permanent Ineff=
       F       F
Bank Sta=211.35,229.66
XS Rating Curve= 0 ,0
Exp/Cntr(USF)=0,0
Exp/Cntr=0.5,0.3

Type RM Length L Ch R = 1 ,10316   ,111.4,111.4,111.4
XS GIS Cut Line= 4
2501124.17978042 623681.142829512501145.03299555623900.101588339
2501151.98406726624062.2932615462501165.88621068 624167.71784913
#Sta/Elev= 30
       0 1942.28    25.9 1935.51      54 1925.68    82.1 1920.74   92.89 1920.26
   122.3 1917.37   150.4  1906.2   170.5 1905.63   182.6 1903.54  190.591903.541
   206.7 1903.07   214.7 1903.79   222.7 1906.02   238.8  1906.1   247.3 1904.28
   278.8 1904.07   294.8 1902.74  302.481900.098   306.8 1899.11   310.8 1898.99
  315.64  1900.1   318.8  1902.2   322.8 1906.34   334.8 1911.56   347.1 1917.85
   362.9 1923.35  386.711928.223   415.2 1934.51   438.8 1940.85   488.6 1955.97
#Mann= 6 ,-1 , 0
       0      .1       0   92.89     .12       0  190.59      .1       0
  302.48    .045       0  315.64      .1       0  386.71      .1       0
#XS Ineff= 2 , 0
             238 1906.53
Permanent Ineff=
       F       F
Bank Sta=302.48,315.64
XS Rating Curve= 0 ,0
Exp/Cntr(USF)=0,0
Exp/Cntr=0.3,0.1

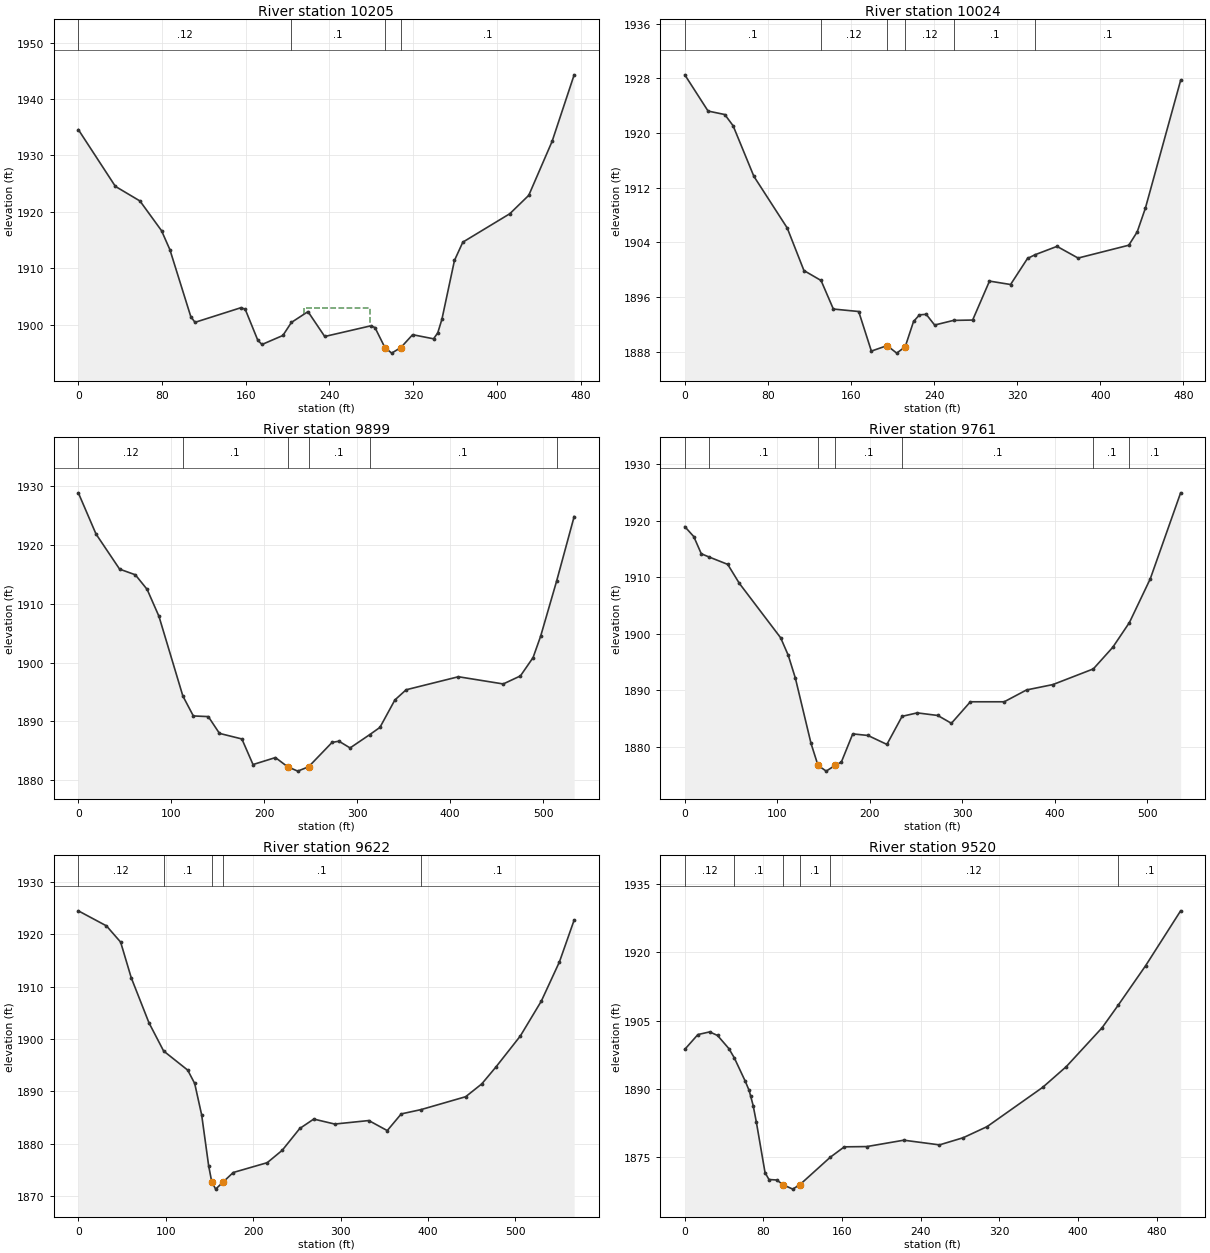
Type RM Length L Ch R = 1 ,10205   ,180.7,180.7,180.7
XS GIS Cut Line= 4
2501032.65733626623683.4598534132501038.44989602623903.577124193
2501038.44989602 624034.488974712501037.29138406624157.291241567
#Sta/Elev= 30
       0 1934.58    35.4 1924.51    58.9 1921.92    79.5 1916.66    87.5 1913.29
   107.5 1901.41   111.5  1900.4   155.5    1903   159.5 1902.72   171.5 1897.24
   175.5 1896.47   195.5 1898.07  203.671900.387   219.5  1902.3   235.5 1897.89
   279.5 1899.78   283.5 1899.48     2931895.934   299.5 1894.94  308.291895.934
   319.5 1898.21   339.5 1897.48   343.5 1898.52   347.5 1900.94   359.5 1911.38
   367.5 1914.62   412.4 1919.66   430.5 1922.92   452.8 1932.48   473.9 1944.29
#Mann= 4 ,-1 , 0
       0     .12       0  203.67      .1       0     293    .045       0
  308.29      .1       0
#XS Ineff= 1 ,-1
  215.36   279.2    1903
Permanent Ineff=
       F
Bank Sta=293,308.29
XS Rating Curve= 0 ,0
Exp/Cntr(USF)=0,0
Exp/Cntr=0.3,0.1

Type RM Length L Ch R = 1 ,10024   ,125.6,125.6,125.6
XS GIS Cut Line= 4
2500927.23274867623676.5087817042500919.12316501623793.518488803
2500883.20929452623997.4165922632500856.56351963624148.023145955
#Sta/Elev= 30
       0 1928.53    22.4 1923.23    38.5 1922.72    46.5 1921.08    66.5 1913.68
    98.6 1906.12   114.7 1899.89  131.171898.438     143 1894.26   167.4  1893.9
   179.6 1888.11   194.8 1888.91     204 1887.81  212.161888.738   220.2 1892.44
   225.9 1893.41   232.4 1893.49   240.5 1891.92  258.72  1892.6   277.1 1892.65
   293.3 1898.35   313.6 1897.85   329.9 1901.66  337.251902.212   358.3 1903.43
   378.6 1901.72   427.4  1903.6   435.5 1905.55   443.4 1909.03   477.3 1927.72
#Mann= 6 ,-1 , 0
       0      .1       0  131.17     .12       0   194.8    .045       0
  212.16     .12       0  258.72      .1       0  337.25      .1       0
Bank Sta=194.8,212.16
XS Rating Curve= 0 ,0
Exp/Cntr(USF)=0,0
Exp/Cntr=0.3,0.1

Type RM Length L Ch R = 1 ,9899    ,137.9,137.9,137.9
XS GIS Cut Line= 4
2500827.60072085623620.9002080332500794.00387425623718.215211957
2500773.15065913623960.3442098162500755.77297986624146.864634003
#Sta/Elev= 30
       0 1928.91      19  1921.9    44.4 1915.91    61.3 1914.95      74 1912.46
    86.7 1907.88  112.431894.298   123.7  1890.9   139.8 1890.79   151.8 1887.93
   175.9 1886.98   187.9 1882.62     212 1883.81   225.11882.245     236  1881.5
   247.71882.245   272.9 1886.39   280.3  1886.6   292.3 1885.45  313.251887.699
   324.4 1888.95   340.5 1893.63   352.6 1895.36   408.8 1897.58     457 1896.35
   475.5 1897.72   489.1 1900.84   497.2 1904.46  514.361913.831   533.3 1924.87
#Mann= 6 ,-1 , 0
       0     .12       0  112.43      .1       0   225.1    .045       0
   247.7      .1       0  313.25      .1       0  514.36      .1       0
Bank Sta=225.1,247.7
XS Rating Curve= 0 ,0
Exp/Cntr(USF)=0,0
Exp/Cntr=0.3,0.1

Type RM Length L Ch R = 1 ,9761    ,139.1,139.1,139.1
XS GIS Cut Line= 4
2500710.59101375623617.4246721792500694.37184643623698.520508782
2500641.08029666623934.8569468832500609.80047397624143.389098149
#Sta/Elev= 30
       0 1918.94     9.7 1917.18    17.8 1914.15   25.631913.616    46.4 1912.27
    58.9 1908.93   103.6  1899.3   111.8 1896.21   119.5 1892.17   136.4 1880.65
  143.931876.766   152.8 1875.75  162.481876.765   169.2 1877.36   181.5 1882.33
   197.9 1882.05   218.4 1880.47   234.8 1885.43   251.2 1886.04   273.4 1885.58
   288.1  1884.2   308.6    1888   345.2    1888   369.3 1890.09   397.8 1891.04
  441.471893.806   462.5 1897.63  480.461901.998     503 1909.72   535.8 1924.91
#Mann= 7 ,-1 , 0
       0     .12       0   25.63      .1       0  143.93    .045       0
  162.48      .1       0   234.8      .1       0  441.47      .1       0
  480.46      .1       0
Bank Sta=143.93,162.48
XS Rating Curve= 0 ,0
Exp/Cntr(USF)=0,0
Exp/Cntr=0.3,0.1

Type RM Length L Ch R = 1 ,9622    ,101.9,101.9,101.9
XS GIS Cut Line= 4
2500559.98446006 623571.084194122500543.76529274623675.350269753
 2500558.8259481623958.0271859132500550.71636444 624136.43802644
#Sta/Elev= 30
       0 1924.52    32.2 1921.64    48.4 1918.53    60.5 1911.73    80.8  1903.1
   97.571897.703   125.1 1894.05   133.1  1891.5   141.1 1885.46   149.1 1875.73
   152.61872.684   157.1 1871.28  165.85 1872.68   177.2 1874.46   216.1 1876.34
   233.2  1878.7   253.3 1882.88   269.3 1884.68   293.3 1883.73   332.3  1884.4
   353.4 1882.48   369.4 1885.67  392.051886.494   443.1 1888.96   461.5 1891.41
   477.6 1894.62   505.6 1900.57   529.6 1907.24   550.4 1914.77   567.2 1922.76
#Mann= 5 ,-1 , 0
       0     .12       0   97.57      .1       0   152.6    .045       0
  165.85      .1       0  392.05      .1       0
Bank Sta=152.6,165.85
XS Rating Curve= 0 ,0
Exp/Cntr(USF)=0,0
Exp/Cntr=0.3,0.1

Type RM Length L Ch R = 1 ,9520    ,218.9,218.9,218.9
XS GIS Cut Line= 4
2500436.02368125  623633.64383952500440.65772905623696.203484879
2500468.46201589623915.1622437082500496.26630272624134.121002537
#Sta/Elev= 30
       0 1898.71    13.3 1901.95    25.3 1902.54    33.3 1901.75    44.8 1898.88
   50.32 1896.85    61.4 1891.75    65.4  1889.7      67 1888.43    69.5 1886.38
    72.7 1882.82    81.6 1871.65    85.6 1870.14    93.7 1870.03   99.521869.031
   109.8 1868.03  117.141869.031  147.931875.031   162.2 1877.31   185.1 1877.37
   222.7 1878.77     259 1877.74   283.2 1879.32   307.4 1881.75     364 1890.38
     388 1894.93   424.3 1903.44  440.641908.375   468.7  1917.1   504.2 1929.11
#Mann= 6 ,-1 , 0
       0     .12       0   50.32      .1       0   99.52    .045       0
  117.14      .1       0  147.93     .12       0  440.64      .1       0
Bank Sta=99.52,117.14
XS Rating Curve= 0 ,0
Exp/Cntr(USF)=0,0
Exp/Cntr=0.3,0.1

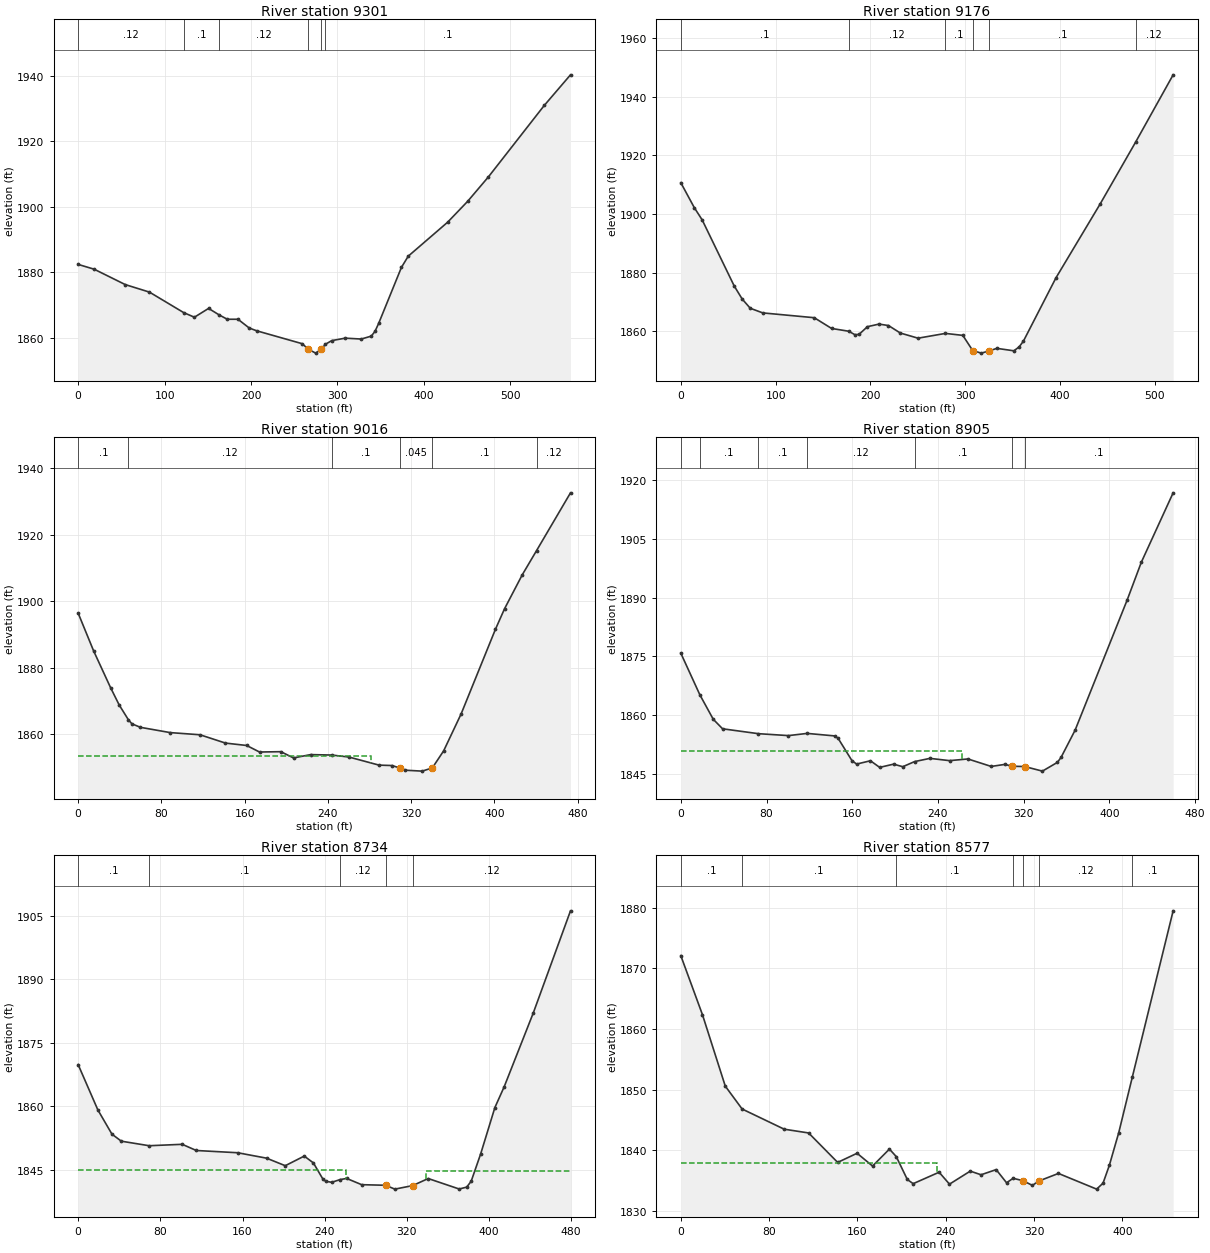
Type RM Length L Ch R = 1 ,9301    ,124.9,124.9,124.9
XS GIS Cut Line= 4
2500258.77135267623624.3757438882500261.08837658623770.348249774
2500354.92784464624017.1112954382500426.75558564 624159.60826547
#Sta/Elev= 30
       0  1882.4    18.5 1880.94    54.5 1876.24    82.5 1873.94  122.111867.685
   134.5 1866.28   150.9 1868.97  163.111866.985   172.5 1865.66   184.9 1865.66
   197.9 1862.99   206.5 1862.14   259.3 1858.19  266.031856.553   274.8 1855.32
  281.521856.552  286.031858.025   293.4 1859.14   308.9 1859.89   327.5 1859.62
   339.1 1860.51   343.4 1861.95   347.7 1864.42     374 1881.49   381.9 1884.92
   427.4 1895.27   450.6 1901.65   474.7 1909.14   539.2 1930.91   569.6 1940.27
#Mann= 6 ,-1 , 0
       0     .12       0  122.11      .1       0  163.11     .12       0
  266.03    .045       0  281.52     .12       0  286.03      .1       0
Bank Sta=266.03,281.52
XS Rating Curve= 0 ,0
Exp/Cntr(USF)=0,0
Exp/Cntr=0.3,0.1

Type RM Length L Ch R = 1 ,9176    ,159.7,159.7,159.7
XS GIS Cut Line= 4
2500082.67753605623661.4481263352500137.12759777623823.639799542
2500226.33301803624007.8431998262500270.35647219624144.547610101
#Sta/Elev= 30
       0 1910.67    14.2 1902.17    22.6 1897.93    56.4 1875.37    64.8 1870.93
    73.3 1867.79    86.5 1866.21   140.8 1864.57   159.1  1860.9  177.161859.953
   183.7 1858.77     188 1858.87   196.9 1861.51   209.1 1862.39   219.1  1861.9
   231.6 1859.34   250.3 1857.58  279.161859.212   297.5 1858.54  307.931853.376
   316.9 1852.48   325.1  1853.2   333.4 1854.11   351.4 1853.27   356.9  1854.6
   361.4 1856.54   395.8 1878.19   442.1 1903.23  479.741924.463   519.4 1947.48
#Mann= 6 ,-1 , 0
       0      .1       0  177.16     .12       0  279.16      .1       0
  307.93    .045       0   325.1      .1       0  479.74     .12       0
Bank Sta=307.93,325.1
XS Rating Curve= 0 ,0
Exp/Cntr(USF)=0,0
Exp/Cntr=0.3,0.1

Type RM Length L Ch R = 1 ,9016    ,110.9,110.9,110.9
XS GIS Cut Line= 4
2499993.47211578 623704.313068542500044.44664165623946.442066398
2500082.67753605624092.4145722842500110.48182288624161.925289373
#Sta/Elev= 30
       0 1896.44    14.9 1885.07    31.2 1874.03    39.4 1868.88   48.291864.413
    51.7 1863.19    59.9 1862.14    88.5 1860.56   117.1 1859.91   141.6 1857.41
     162 1856.69   174.3 1854.73   194.8 1854.83     207 1852.95   223.4 1853.95
  243.64 1853.82   260.3 1853.22   289.2 1850.79   301.7 1850.67  308.981849.941
   314.1 1849.27   330.6 1848.99  340.361849.941   351.3 1855.09   368.1 1866.19
     401 1891.55   409.8 1897.75   426.8 1907.93  440.581915.221   473.2 1932.57
#Mann= 6 ,-1 , 0
       0      .1       0   48.29     .12       0  243.64      .1       0
  308.98    .045       0  340.36      .1       0  440.58     .12       0
#XS Ineff= 2 , 0
          281.89 1853.65
Permanent Ineff=
       F       F
Bank Sta=308.98,340.36
XS Rating Curve= 0 ,0
Exp/Cntr(USF)=0,0
Exp/Cntr=0.3,0.1

Type RM Length L Ch R = 1 ,8905    ,171.8,171.8,171.8
XS GIS Cut Line= 4
2499844.02407404623758.7631302592499921.64437479623951.076114204
2499986.52104408624103.9996917992500023.59342652624181.619992548
#Sta/Elev= 30
       0 1875.84   17.811865.177    30.3 1858.93      39  1856.5   72.481855.249
   100.5 1854.76  117.971855.322   143.6 1854.68   146.8 1854.08   159.7 1848.38
   164.1 1847.48     177 1848.33   185.6 1846.64   198.6 1847.46   207.2 1846.81
  218.181848.117   232.5 1848.94   250.8 1848.36     268 1848.79   289.7 1846.88
   302.7 1847.41   308.8 1846.93     321 1846.85   337.5 1845.68   351.5 1847.92
   354.9 1849.19     368 1856.14   416.6 1889.42   429.8 1899.06   459.5 1916.81
#Mann= 7 ,-1 , 0
       0      .1       0   17.81      .1       0   72.48      .1       0
  117.97     .12       0  218.18      .1       0   308.8    .045       0
     321      .1       0
#XS Ineff= 2 , 0
             262 1850.92
Permanent Ineff=
       F       F
Bank Sta=308.8,321
XS Rating Curve= 0 ,0
Exp/Cntr(USF)=0,0
Exp/Cntr=0.3,0.1

Type RM Length L Ch R = 1 ,8734    ,156.6,156.6,156.6
XS GIS Cut Line= 4
2499684.14942474623834.0664071052499783.78145257624015.952783487
2499883.41348039624185.0955284022499918.16883894624252.289221588
#Sta/Elev= 30
       0 1869.86    19.2 1859.16    32.9 1853.45      42 1851.79   69.111850.716
   101.3 1851.05     115 1849.59   155.3 1849.06   183.4 1847.78   201.6    1846
   220.1 1848.27     229 1846.66     238 1842.95   240.9 1842.34   246.8 1842.08
  255.121842.731   261.4 1842.99     276 1841.52   299.3 1841.38   308.3 1840.47
   325.6  1841.3   340.8 1842.97   370.9  1840.5   378.2 1840.94   382.6 1842.32
   391.8 1848.75   405.7 1859.74   414.7 1864.61   443.1 1882.08   479.3 1906.17
#Mann= 5 ,-1 , 0
       0      .1       0   69.11      .1       0  255.12     .12       0
   299.3    .045       0   325.6     .12       0
#XS Ineff= 2 , 0
          260.63 1844.91  338.82         1844.65
Permanent Ineff=
       F       F
Bank Sta=299.3,325.6
XS Rating Curve= 0 ,0
Exp/Cntr(USF)=0,0
Exp/Cntr=0.3,0.1

Type RM Length L Ch R = 1 ,8577    ,136.8,136.8,136.8
XS GIS Cut Line= 4
 2499570.6152535623925.5888512712499642.44299449624083.146476672
2499752.50162988  624261.55731722499794.20806013 624309.05630721
#Sta/Elev= 30
       0 1872.11    19.6 1862.37    40.3 1850.57   55.561846.791    93.7 1843.46
   115.8 1842.84   142.1 1837.98   159.7 1839.49   173.7 1837.38     189 1840.18
  195.221838.932   205.2 1835.16   210.5 1834.47     234 1836.36   243.4 1834.39
   262.2 1836.54     272 1835.94   285.7 1836.79   295.1 1834.62  301.051835.355
   309.8 1834.97   318.5 1834.19   324.51834.917   342.1 1836.16   376.7 1833.57
   382.5 1834.55   388.2 1837.49   396.7 1842.87  409.111852.125     446  1879.5
#Mann= 7 ,-1 , 0
       0      .1       0   55.56      .1       0  195.22      .1       0
  301.05     .12       0   309.8    .045       0   324.5     .12       0
  409.11      .1       0
#XS Ineff= 2 , 0
          232.51 1837.93
Permanent Ineff=
       F       F
Bank Sta=309.8,324.5
XS Rating Curve= 0 ,0
Exp/Cntr(USF)=0,0
Exp/Cntr=0.3,0.1

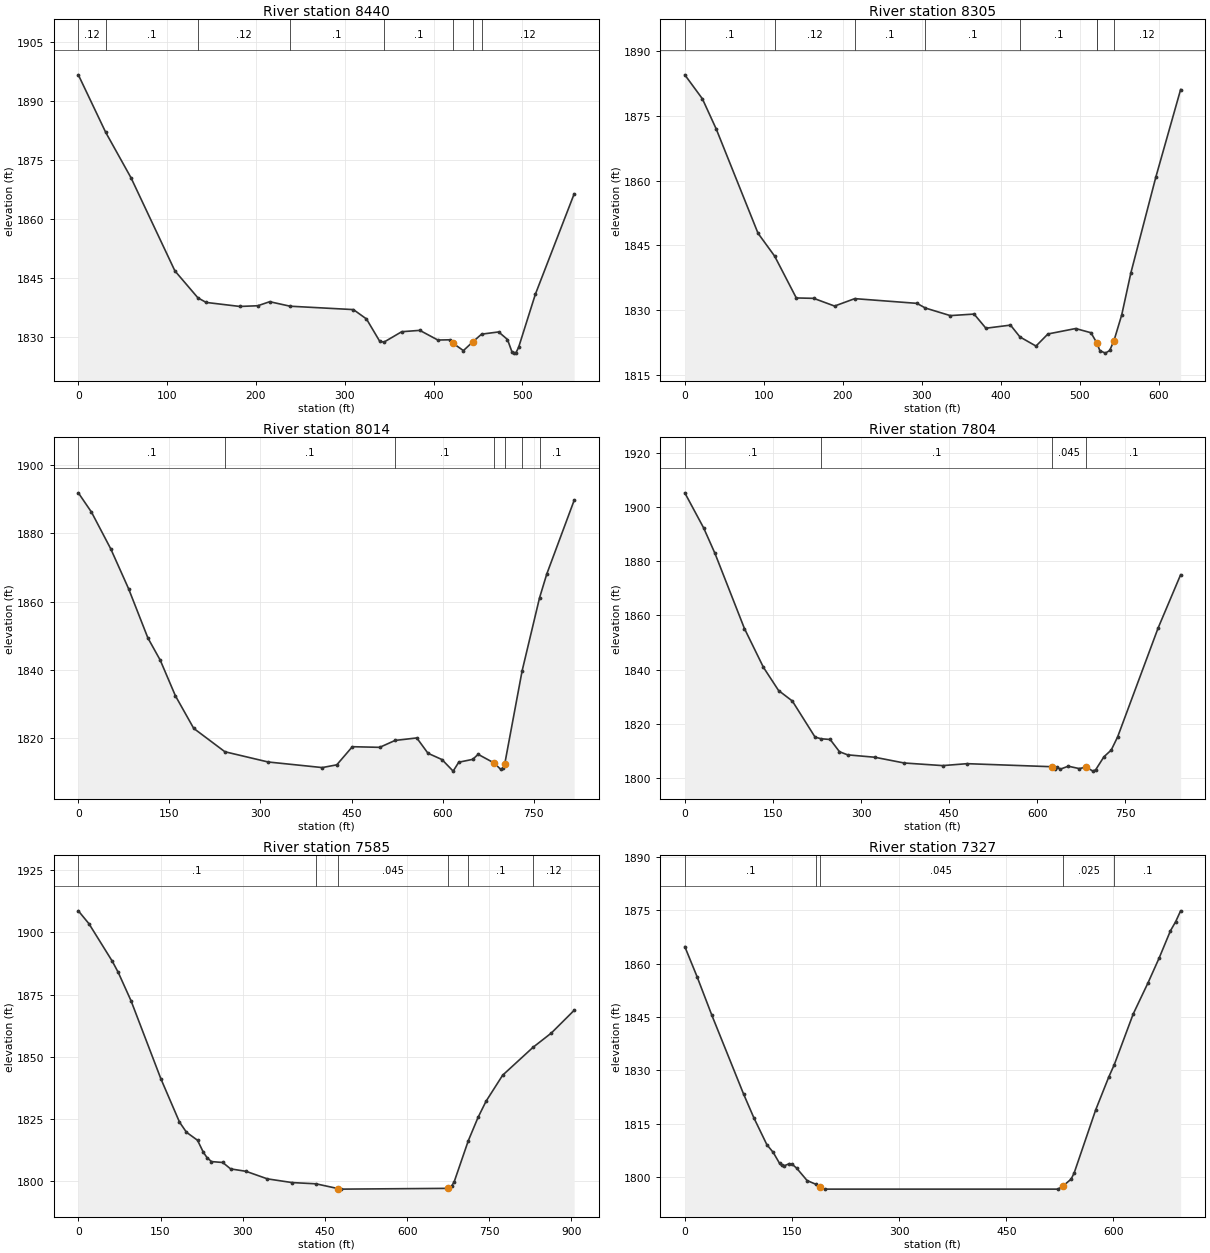
Type RM Length L Ch R = 1 ,8440    ,135.3,135.3,135.3
XS GIS Cut Line= 4
2499393.46269411623915.6112050452499542.81096666624187.412552305
2499644.76001839624326.4339864822499693.41752035624384.359584056
#Sta/Elev= 30
       01896.565   30.861881.935  59.3251870.407 108.7161846.763  134.631839.913
 143.8691838.753 181.741 1837.73 202.0131837.906  215.441838.935   238.4 1837.79
 309.6981836.928 324.3641834.554 339.2451828.899  344.061828.667 364.047 1831.31
 384.4231831.656 404.715  1829.2 418.4551829.261 421.3171828.467 433.4911826.509
  444.211828.764  453.951830.691 473.1731831.255 483.1241829.331 488.3481826.071
 489.9381825.872 492.7781826.026 495.6171827.318 514.4671840.807 558.1771866.324
#Mann= 8 ,-1 , 0
       0     .12       0   30.86      .1       0  134.63     .12       0
   238.4      .1       0  344.06      .1       0 421.317    .045       0
  444.21      .1       0  453.95     .12       0
Bank Sta=421.317,444.21
XS Rating Curve= 0 ,0
Exp/Cntr(USF)=0,0
Exp/Cntr=0.3,0.1

Type RM Length L Ch R = 1 ,8305    ,291.2,291.2,291.2
XS GIS Cut Line= 4
 2499304.9121543623946.6898941752499464.03215396624291.678627938
2499590.30995667624426.0660143092499640.12597058624465.455420659
#Sta/Elev= 30
       01884.557  22.2461879.008  39.8661871.969  92.726 1847.82  113.791842.514
  141.18 1832.82 163.2051832.732 189.6351830.943  215.221832.663 293.9451831.568
  304.671830.482 336.1491828.728 366.2941829.084 381.2781825.802 412.4061826.524
   424.41823.779 444.7011821.666 459.8151824.469 494.8631825.729 514.2791824.758
  521.411822.497 521.545 1822.43 525.5981820.605 532.5231820.028 538.0111820.639
   543.51822.955 553.2761828.908 564.878 1838.67 596.5451860.909 627.8311881.152
#Mann= 8 ,-1 , 0
       0      .1       0  113.79     .12       0  215.22      .1       0
  304.67      .1       0   424.4      .1       0  521.41     .12       0
 521.545    .045       0   543.5     .12       0
Bank Sta=521.545,543.5
XS Rating Curve= 0 ,0
Exp/Cntr(USF)=0,0
Exp/Cntr=0.3,0.1

Type RM Length L Ch R = 1 ,8014    ,209.2,209.2,209.2
XS GIS Cut Line= 4
2499002.13507747624013.6309740212499292.57238514624479.357564077
2499385.25334126624641.5492372842499443.17893883624698.316322906
#Sta/Elev= 30
       01891.914  21.6811886.253   53.341875.516  82.6531863.863 114.6231849.359
 134.9151842.867 159.8961832.428  190.081822.876  241.441816.024 312.6141813.025
 401.7891811.385 425.751 1812.19 451.3891817.501 496.4621817.317  521.771819.338
 557.5441820.071 575.9721815.579 599.0071813.736 617.4351810.344 626.6491812.953
 649.6841813.795 658.5921815.267 684.9771812.726 695.7541810.863 700.3611811.155
 702.5671812.579  731.031839.728  759.73 1861.12 771.6181868.099 816.7761889.711
#Mann= 7 ,-1 , 0
       0      .1       0  241.44      .1       0  521.77      .1       0
 684.977    .045       0 702.567      .1       0  731.03     .12       0
  759.73      .1       0
Bank Sta=684.977,702.567
XS Rating Curve= 0 ,0
Exp/Cntr(USF)=0,0
Exp/Cntr=0.3,0.1

Type RM Length L Ch R = 1 ,7804    ,219.1,219.1,219.1
XS GIS Cut Line= 4
2498848.45685023624107.0665797842499117.63708047624572.038520195
2499227.69571586624755.0834085282499275.19470587 624835.02073318
#Sta/Elev= 30
       01905.155  32.1511892.193   51.311882.858  101.481855.168 133.8331840.869
 159.6191832.319 183.0381828.453  221.651815.174  231.781814.551 247.4381814.283
 263.2481809.775 277.1131808.625 323.3331807.741 373.3111805.624 438.8811804.662
 480.4791805.373 624.6091804.251 629.2761803.453 633.9441804.002 639.2571803.367
 652.613 1804.44 671.2831803.561 682.9791804.117 694.6191802.626 699.2871803.134
 713.2891807.899  725.721810.383 736.6261815.232 805.4721855.324 843.8371874.983
#Mann= 4 ,-1 , 0
       0      .1       0  231.78      .1       0 624.609    .045       0
 682.979      .1       0
Bank Sta=624.609,682.979
XS Rating Curve= 0 ,0
Exp/Cntr(USF)=0,0
Exp/Cntr=0.3,0.1

Type RM Length L Ch R = 1 ,7585    ,258.6,258.6,258.6
XS GIS Cut Line= 4
2498640.22560171 624258.881530022498895.20278578624628.805605817
2499035.38273191624859.3494841612499209.81919066624923.218890459
#Sta/Elev= 30
       01908.716  19.4441903.501  62.2121888.325  72.8831883.894  96.0671872.561
 150.6141841.102 184.6211823.645 197.378 1819.55 217.5091816.334 228.3441811.418
 234.7641809.387 242.9181807.745 263.5231807.386 277.9031804.806 306.0741803.825
 344.9391800.793 390.0621799.294  433.63  1798.8  473.76 1796.88 479.8141796.656
 674.6351796.963 681.1141797.873 685.7951799.526  711.721816.177 729.4021825.501
 743.9811832.011 774.3721842.533  829.821853.757 863.2521859.514 904.8631868.654
#Mann= 6 ,-1 , 0
       0      .1       0  433.63    .025       0  473.76    .045       0
 674.635     .12       0  711.72      .1       0  829.82     .12       0
Bank Sta=473.76,674.635
XS Rating Curve= 0 ,0
Exp/Cntr(USF)=0,0
Exp/Cntr=0.3,0.1

Type RM Length L Ch R = 1 ,7327    ,221.3,221.3,221.3
XS GIS Cut Line= 4
2498545.33217644624493.2597074952498625.26950109 624646.18328509
2498802.52182967624978.6762151632498895.20278578625089.893362505
#Sta/Elev= 30
       0 1864.75    17.1 1856.34    37.9 1845.46    82.3 1823.35    96.6 1816.72
   114.9 1809.13   123.8 1806.97   132.7 1803.88   135.6 1803.32   138.6 1803.15
   146.3 1803.81   150.5  1803.6   156.4 1802.59   171.2 1799.07   183.31798.039
     189 1797.37     196 1796.66   522.4 1796.66     529 1797.46   540.8 1799.47
   545.1 1801.22   575.2 1818.91   593.4 1828.09  601.281831.625   627.7 1845.83
   648.6 1854.64   664.2 1861.62   679.8 1869.17   687.2 1871.76   694.1 1874.79
#Mann= 5 ,-1 , 0
       0      .1       0   183.3    .025       0     189    .045       0
     529    .025       0  601.28      .1       0
Bank Sta=189,529
XS Rating Curve= 0 ,0
Exp/Cntr(USF)=0,0
Exp/Cntr=0.5,0.3

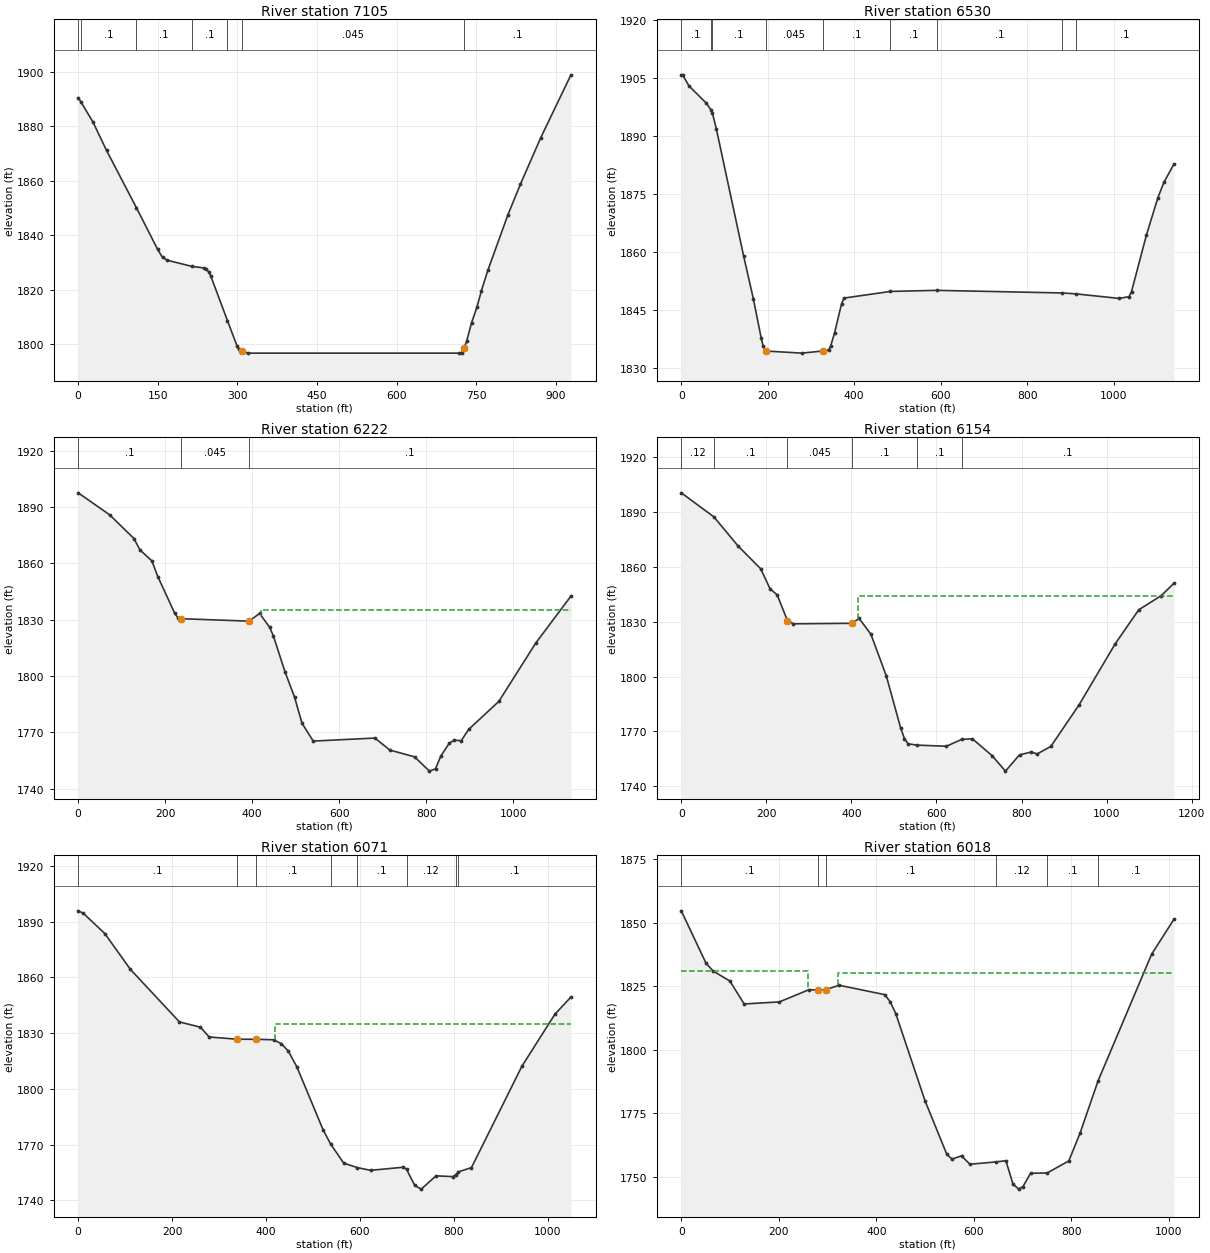
Type RM Length L Ch R = 1 ,7105    ,576,576,576
XS GIS Cut Line= 4
2498273.08186784624508.3203628642498394.72562275 624724.96209779
2498669.29295525 625180.257294722498763.13242332625294.949977916
#Sta/Elev= 30
       0 1890.49    5.691888.806    27.9 1881.56    53.4 1871.13  109.821850.057
   149.7 1834.78   158.9 1831.81   168.1 1830.78  213.941828.547   236.9 1827.96
   241.5  1827.6   246.1 1826.42   249.9 1824.92  281.261808.593   299.4 1799.22
   302.3  1798.2   308.2 1797.43   319.8 1796.66   717.8 1796.66   722.5 1796.76
   727.2 1798.71   731.8 1801.03   741.2 1807.89   751.1 1813.47   759.7 1819.65
   771.8  1827.1   809.4 1847.41     833 1858.69   871.4  1875.8   928.3 1898.92
#Mann= 7 ,-1 , 0
       0     .12       0    5.69      .1       0  109.82      .1       0
  213.94      .1       0  281.26      .1       0   308.2    .045       0
   727.2      .1       0
Bank Sta=308.2,727.2
XS Rating Curve= 0 ,0
Exp/Cntr(USF)=0,0
Exp/Cntr=0.5,0.3

Type RM Length L Ch R = 1 ,6530    ,113,113,113
XS GIS Cut Line= 5
2498035.28656284624488.2966995052498085.34572124 624559.80978293
2498216.92979474624822.9779299322498597.37939856625403.664167338
2498628.84515526625459.444372409
#Sta/Elev= 30
       0 1905.82     3.2 1905.78    17.8 1902.95    56.9 1898.61   68.641896.798
   71.761896.015    81.3 1891.75   144.3  1858.9   166.8 1847.83   184.7 1837.83
   189.1 1835.76  195.651834.357   278.6 1833.81  327.171834.357   341.1 1834.66
   345.6 1835.68   354.6 1839.05   370.9 1846.64   376.8 1848.06  483.821849.775
  590.921850.053  881.19 1849.38  912.24 1849.15  1012.5 1847.97  1035.7 1848.41
  1041.5 1849.75  1075.7 1864.27  1102.4    1874  1116.2 1877.97  1139.8 1882.77
#Mann= 9 ,-1 , 0
       0      .1       0   68.64    .055       0   71.76      .1       0
  195.65    .045       0  327.17      .1       0  483.82      .1       0
  590.92      .1       0  881.19      .1       0  912.24      .1       0
Bank Sta=195.65,327.17
XS Rating Curve= 0 ,0
Exp/Cntr(USF)=0,0
Exp/Cntr=0.5,0.3

Type RM Length L Ch R = 1 ,6222    ,77.2,66.8,47.1
XS GIS Cut Line= 4
2497748.17479709624651.971764011 2497987.2864105624986.168697376
2498238.98284567625345.5352742582498457.11975615625525.917719464
#Sta/Elev= 30
       0 1897.54    72.4 1885.83   128.2 1873.21   141.9 1867.19   169.4 1861.32
   183.1 1852.96   221.8 1833.47   229.8 1830.95   237.21830.552     3931829.255
     417 1833.36   439.8 1826.09   448.7 1821.41   475.3 1802.37   497.6 1788.66
   514.4 1774.98   540.3 1765.43   681.9 1767.04   716.8 1760.62   773.2 1757.05
   807.4 1749.44   821.4 1750.67   833.2 1757.27   853.3 1764.41   864.9 1765.93
   880.5 1765.62   897.7 1771.68   966.9 1786.53  1051.8 1817.59  1132.7 1842.58
#Mann= 3 , 0 , 0
       0      .1       0   237.2    .045       0     393      .1       0
#XS Ineff= 2 , 0
                          420.82         1835.44
Permanent Ineff=
       F       F
Bank Sta=237.2,393
XS Rating Curve= 0 ,0
Exp/Cntr(USF)=0,0
Exp/Cntr=0.3,0.1

Type RM Length L Ch R = 1 ,6154    ,83.3,83.3,83.3
XS GIS Cut Line= 4
2497654.83695902624747.1740615022497784.99077085 624853.01342497
2497973.78531109625031.7961335312498335.87195028625666.424665666
#Sta/Elev= 30
       01900.637   76.59 1887.48 133.9281871.405 186.6991859.039 208.734 1848.06
 225.2611844.806   249.6 1830.67 263.5651828.876   401.51829.164 418.0721831.845
 445.8481823.136 481.9891800.366 515.7761771.821 524.5731766.057  533.371763.139
  555.321762.419 623.4241761.835  659.711765.619 684.6211765.865 730.6731756.674
 762.0861748.187 795.1471757.085 822.7791758.662 836.5941757.604 868.8311761.714
  935.091784.4641020.1251817.9371075.4361836.5571128.6191844.3691158.4261851.147
#Mann= 6 ,-1 , 0
       0     .12       0   76.59      .1       0   249.6    .045       0
   401.5      .1       0  555.32      .1       0  659.71      .1       0
#XS Ineff= 2 , 0
                          414.81         1844.28
Permanent Ineff=
       F       F
Bank Sta=249.6,401.5
XS Rating Curve= 0 ,0
Exp/Cntr(USF)=0,0
Exp/Cntr=0.3,0.1

Type RM Length L Ch R = 1 ,6071    ,53.2,53.2,53.2
XS GIS Cut Line= 5
2497607.63832396624818.6871449262497753.52501415624924.526508394
2497910.85379768625078.9947685912498151.13775799625485.189082442
2498224.18336438625645.991957109
#Sta/Elev= 30
       01895.824  10.9621894.508  56.7861883.567 111.2021864.302 215.5791836.026
 260.4251833.151 278.9411827.906   338.3 1826.71   377.91826.669 416.2181826.416
 432.6841824.268 447.2851820.367 465.6631811.834 521.4321777.982  537.611770.264
  565.491759.984  594.261757.602  622.491756.123 692.572  1757.8  699.291756.641
 716.6251748.024 730.5681746.004 761.9011753.169 797.6951752.729  804.331753.837
  809.831755.321 837.4591757.603 944.8251812.1421015.1181840.1581049.2781849.419
#Mann= 8 ,-1 , 0
       0      .1       0   338.3    .045       0   377.9      .1       0
  537.61      .1       0  594.26      .1       0  699.29     .12       0
  804.33      .1       0  809.83      .1       0
#XS Ineff= 2 , 0
                          418.11         1834.76
Permanent Ineff=
       F       F
Bank Sta=338.3,377.9
XS Rating Curve= 0 ,0
Exp/Cntr(USF)=0,0
Exp/Cntr=0.5,0.3

Type RM Length L Ch R = 1 ,6018    ,62,62,62
XS GIS Cut Line= 4
2497573.31204392624987.458021808 2497769.2578925625093.297385276
2497865.08542429625061.8316285692498206.07535473625658.302573241
#Sta/Elev= 30
       01854.652   50.821834.004  65.5791830.933  99.8061826.995 128.9231817.982
 201.3621818.806  262.161823.625   279.71823.432   295.81823.562 323.5651825.356
 416.9351821.675 428.163 1818.95 439.8891814.206  499.87 1779.89 544.5181758.848
  555.161756.893 574.7421758.207  592.021754.882  646.091755.813  665.741756.292
 680.2781747.103 692.0051745.086 700.799 1746.11 716.4221751.322  750.511751.452
  794.751756.191 817.7871767.079  854.941787.765 964.642 1837.571010.6251851.384
#Mann= 6 ,-1 , 0
       0      .1       0   279.7    .045       0   295.8      .1       0
  646.09     .12       0  750.51      .1       0  854.94      .1       0
#XS Ineff= 2 , 0
          260.08 1830.77  322.36         1830.33
Permanent Ineff=
       F       F
Bank Sta=279.7,295.8
XS Rating Curve= 0 ,0
Exp/Cntr(USF)=0,0
Exp/Cntr=0.5,0.3