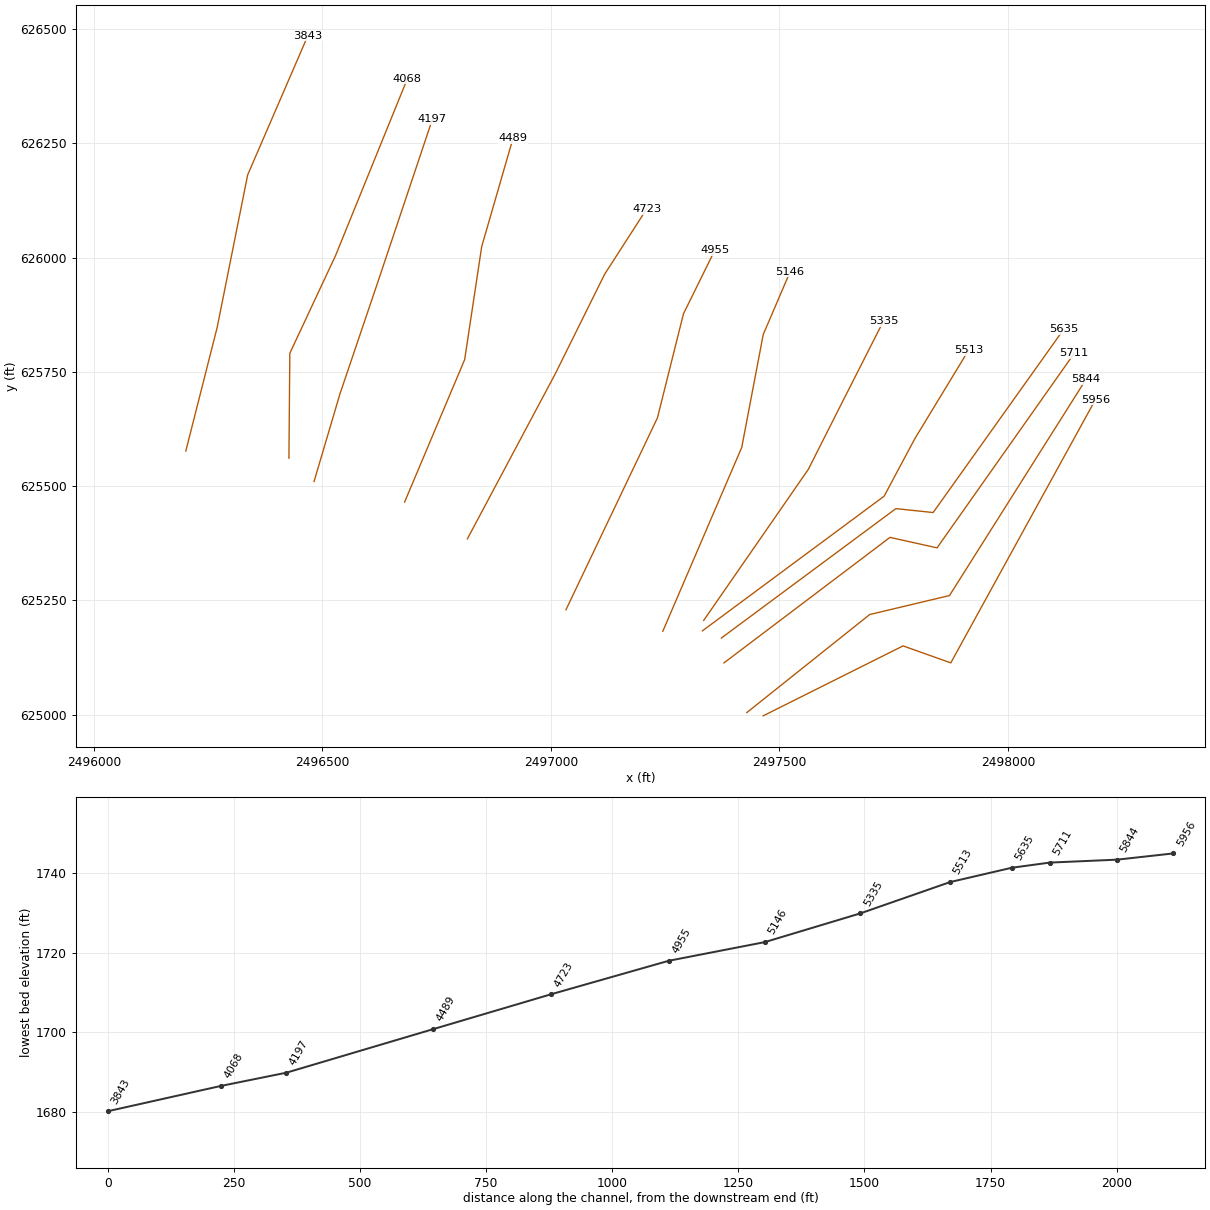
HEC-RAS study LROUGHRN.prj: LROUGHRN

--- LROUGHRN.g01 (geometry) --- (continued)

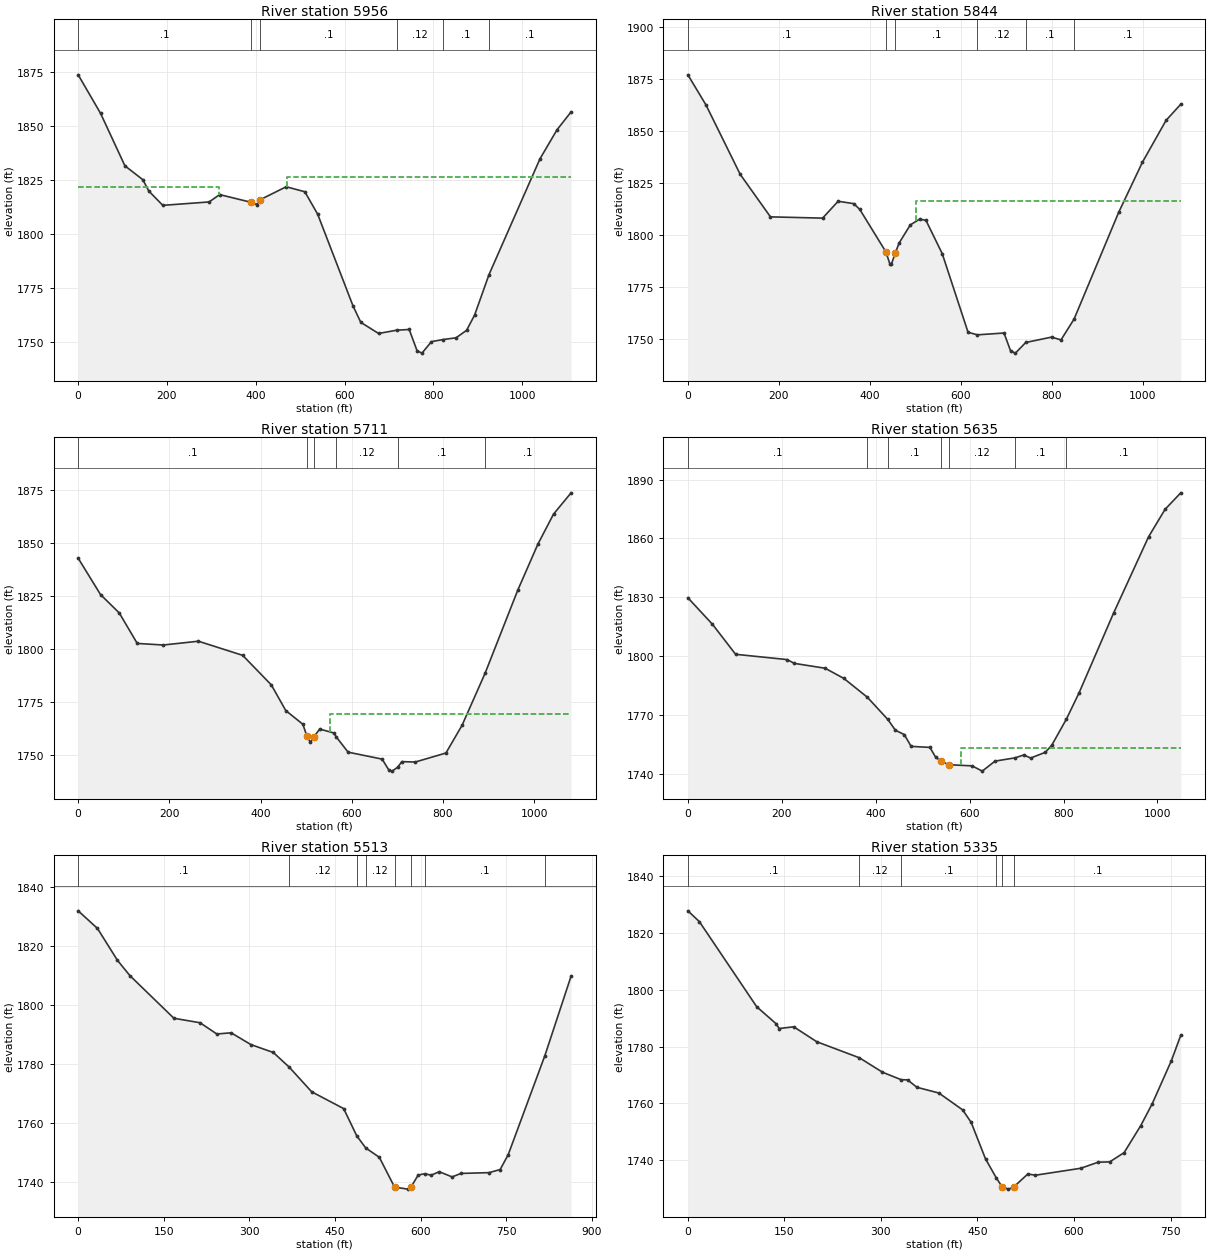
Type RM Length L Ch R = 1 ,5956    ,111.7,111.7,111.7
XS GIS Cut Line= 4
2497464.61215711624997.4698534872497770.68815417625150.507852016
2497875.09725597625113.3210486352498191.51778306625689.232505518
#Sta/Elev= 30
       0 1873.54  50.3521855.746 105.244 1831.46 145.757 1825.02 158.9091819.841
 190.4791813.177 294.8291814.745  318.681818.145     3891814.608  401.711813.565
   410.21815.812  468.521821.779 510.4531819.465 539.3561809.098 619.132  1766.6
 636.5611759.055  676.591753.915  717.761755.447 745.5481755.767 763.2211745.945
 774.3071744.829 795.6231750.136  821.531751.104 851.0331751.914 874.7141755.355
 892.8271762.419   925.31781.1621040.1071834.708  1078.41848.1051110.1491856.403
#Mann= 6 ,-1 , 0
       0      .1       0     389    .045       0   410.2      .1       0
  717.76     .12       0  821.53      .1       0   925.3      .1       0
#XS Ineff= 2 , 0
           317.7 1821.62  470.78         1826.27
Permanent Ineff=
       F       F
Bank Sta=389,410.2
XS Rating Curve= 0 ,0
Exp/Cntr(USF)=0,0
Exp/Cntr=0.5,0.3

Type RM Length L Ch R = 1 ,5844    ,133.6,133.6,133.6
XS GIS Cut Line= 4
 2497428.8556154 625004.621161832497697.74480908625219.160412103
2497872.23673263625260.6380004892498171.31551156625734.260531882
#Sta/Elev= 30
       01876.878  39.9611862.352 114.9951829.115 181.5191808.688 296.123 1808.08
 330.2781816.175 364.5271815.038 377.9091812.257   435.51791.794 443.6921786.289
 447.573 1786.07     4561791.358 464.2491796.084 488.9181804.822 509.4751807.592
 523.3431807.015 559.1231791.033 615.8921753.276  636.361752.046 694.9771752.923
 709.4751744.292 719.9691743.265  742.681748.374 799.3651750.951 820.2151749.622
  848.991759.621 947.0451810.879 999.0831834.8681051.122    18551083.4921862.757
#Mann= 6 ,-1 , 0
       0      .1       0   435.5    .045       0     456      .1       0
  636.36     .12       0  742.68      .1       0  848.99      .1       0
#XS Ineff= 2 , 0
                          502.06         1816.46
Permanent Ineff=
       F       F
Bank Sta=435.5,456
XS Rating Curve= 0 ,0
Exp/Cntr(USF)=0,0
Exp/Cntr=0.5,0.3

Type RM Length L Ch R = 1 ,5711    ,75.2,75.2,75.2
XS GIS Cut Line= 4
  2497378.796457625113.321048635 2497742.0829208625387.931288985
2497845.06176093625365.0471022892498144.98314818625790.321606395
#Sta/Elev= 30
       01842.736  49.0371825.624  90.1911816.958 129.5871802.625   186.71801.886
 263.8021803.673 360.8931797.018 423.7171783.102 455.3991771.032 492.9551764.579
   501.21759.291 509.3451756.071   517.21758.716 529.8331762.325  560.891760.491
  566.121758.638 592.1241751.454 666.7541748.184 681.7971742.944 688.7381742.528
  700.921744.379 709.986    1747 739.3541746.812 806.7251751.047 842.1421764.114
   892.71788.629 964.5091827.7991008.5611849.4011042.7721863.4941081.2851873.513
#Mann= 6 ,-1 , 0
       0      .1       0   501.2    .045       0   517.2      .1       0
  566.12     .12       0  700.92      .1       0   892.7      .1       0
#XS Ineff= 2 , 0
                          552.81         1769.45
Permanent Ineff=
       F       F
Bank Sta=501.2,517.2
XS Rating Curve= 0 ,0
Exp/Cntr(USF)=0,0
Exp/Cntr=0.5,0.3

Type RM Length L Ch R = 1 ,5635    ,122.5,122.5,122.5
XS GIS Cut Line= 4
2497373.07541033625167.6709920382497754.95527582625450.862802398
2497836.48019092625442.281232387 2498122.1507904625843.164941286
#Sta/Elev= 30
       01829.686  52.4121816.141 101.6761800.843 211.2321798.146 227.0091796.198
 292.2941793.732 332.3261788.518   382.31778.914  425.821767.601 441.8971762.124
 460.9991759.846 475.426 1753.87 515.4361753.343 527.5021748.398   539.61746.152
   556.11744.507  605.35 1743.92 626.9141741.237 654.1061746.342  696.981748.023
 715.3241749.488  730.061747.918  761.191750.846 774.976 1754.47  806.111767.788
 833.2051781.259 906.4881821.829 981.0551860.7851016.218  1874.81049.6571883.227
#Mann= 7 ,-1 , 0
       0      .1       0   382.3     .12       0  425.82      .1       0
   539.6    .045       0   556.1     .12       0  696.98      .1       0
  806.11      .1       0
#XS Ineff= 2 , 0
                          581.07         1752.99
Permanent Ineff=
       F       F
Bank Sta=539.6,556.1
XS Rating Curve= 0 ,0
Exp/Cntr(USF)=0,0
Exp/Cntr=0.5,0.3

Type RM Length L Ch R = 1 ,5513    ,177.7,177.7,177.7
XS GIS Cut Line= 4
2497331.59782194625183.4038703912497729.21056578  625478.0377741
 2497796.4328642625603.9008009272497913.71432102625796.986126173
#Sta/Elev= 30
       0 1831.79    33.8 1825.83    68.6  1815.1    90.5 1809.89   167.7 1795.44
   213.5 1793.93   242.9 1790.12   267.9 1790.53   302.6 1786.54   341.8 1783.87
  369.531778.946     409 1770.58   465.1 1764.88  487.941755.693  503.72 1751.57
   527.6  1748.4  554.251738.326   577.5 1737.64  583.051738.324   595.6 1742.39
  607.051742.856   618.3 1742.36   632.6 1743.53   655.1 1741.77   670.5 1742.95
     720 1743.22   739.3 1744.28   753.4 1749.32  817.46 1782.74   863.5  1809.7
#Mann= 8 ,-1 , 0
       0      .1       0  369.53     .12       0  487.94      .1       0
  503.72     .12       0  554.25    .045       0  583.05     .12       0
  607.05      .1       0  817.46      .1       0
Bank Sta=554.25,583.05
XS Rating Curve= 0 ,0
Exp/Cntr(USF)=0,0
Exp/Cntr=0.3,0.1

Type RM Length L Ch R = 1 ,5335    ,189.2,189.2,189.2
XS GIS Cut Line= 4
2497334.45834528625206.2880570872497563.30021224625536.678502508
2497630.52251066625669.6928376772497727.78030411625861.347901255
#Sta/Elev= 30
       0 1827.79    17.9 1823.98     107 1794.01     137 1788.06   141.8 1786.35
   164.5 1786.96   200.2 1781.71  266.651776.036   302.4 1770.97  331.491768.327
   341.3 1768.28   355.9 1765.66     390 1763.65     427  1757.7   440.2 1753.31
   462.5 1740.46  479.061733.841   488.11730.676   498.2 1729.81   506.81730.674
   528.2 1735.13   540.1 1734.71   610.6 1737.16   637.5 1739.29   655.5  1739.4
   677.9 1742.67   703.8  1752.2   721.6  1759.9   751.4 1775.08   765.9 1783.98
#Mann= 6 ,-1 , 0
       0      .1       0  266.65     .12       0  331.49      .1       0
  479.06      .1       0   488.1    .045       0   506.8      .1       0
Bank Sta=488.1,506.8
XS Rating Curve= 0 ,0
Exp/Cntr(USF)=0,0
Exp/Cntr=0.3,0.1

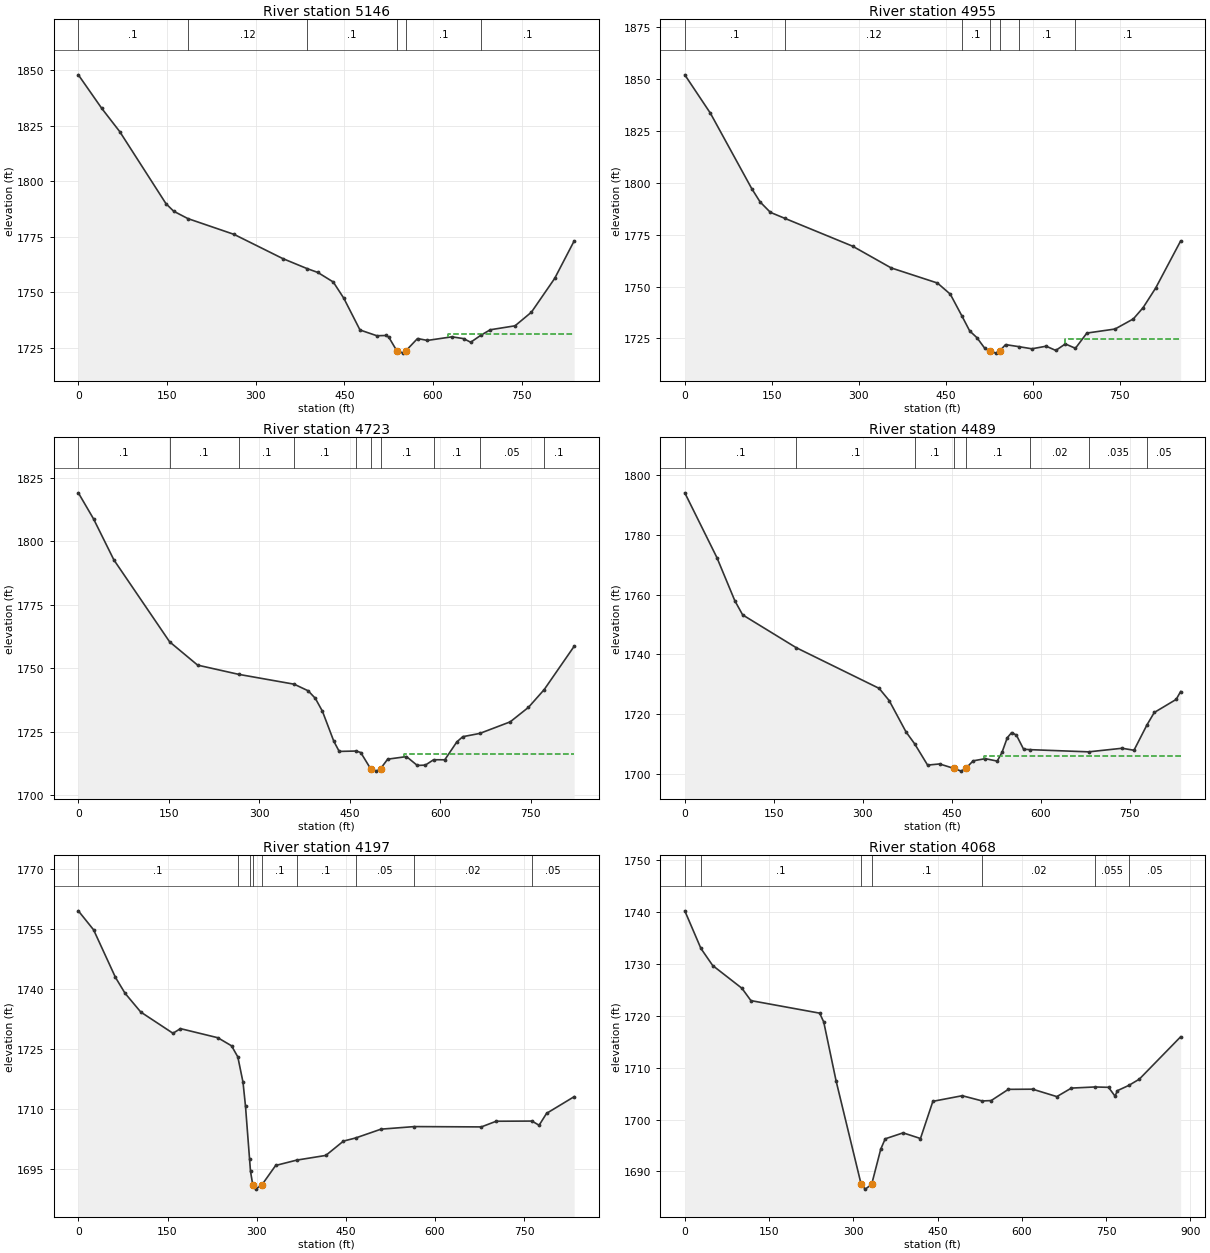
Type RM Length L Ch R = 1 ,5146    ,190.6,190.6,190.6
XS GIS Cut Line= 4
2497245.00715152625182.5543459712497417.65876582625584.754129291
2497464.74556972 625831.95984977 2497523.6040746625969.296361148
#Sta/Elev= 30
       0 1847.92    39.5 1832.86      70 1822.37   148.4 1789.86   161.4  1786.5
  185.371783.186   263.5 1776.08   345.7 1765.21  386.77  1760.7   405.2 1758.94
   431.3 1754.64   449.1 1747.34   476.5 1733.04     505 1730.45   521.3 1730.57
   525.4 1729.71  538.551723.773   549.7 1722.62  554.481723.773   573.8 1729.19
   590.5 1728.34     632 1729.96   651.6 1729.16   663.8 1727.52  681.121730.694
   696.9 1733.14   738.8 1734.92   766.5 1741.05   805.8 1756.24   838.8 1773.13
#Mann= 6 ,-1 , 0
       0      .1       0  185.37     .12       0  386.77      .1       0
  538.55    .045       0  554.48      .1       0  681.12      .1       0
#XS Ineff= 2 , 0
                          625.51         1731.37
Permanent Ineff=
       F       F
Bank Sta=538.55,554.48
XS Rating Curve= 0 ,0
Exp/Cntr(USF)=0,0
Exp/Cntr=0.3,0.1

Type RM Length L Ch R = 1 ,4955    ,232.8,232.8,232.8
XS GIS Cut Line= 4
2497033.11653396625229.6411498712497233.23545054625649.498484654
2497290.13200526625877.0847035092497358.80026095626016.383165049
#Sta/Elev= 30
       0  1852.1    44.2 1833.57   115.3  1797.3   129.9 1790.81   147.6  1785.8
  172.771782.883   289.4 1769.49   355.9 1759.01   435.6 1751.74   457.8 1746.37
   477.71735.942   491.3 1728.63   503.7 1725.41     517 1720.37   525.61718.994
   536.8 1717.94  543.051718.993   553.1 1722.04  575.641721.081   598.5 1720.03
   623.2 1721.28   639.7 1719.24   656.2 1722.37  673.581720.272   693.3 1727.61
   741.9 1729.56   773.5 1734.44   790.3 1739.87     812 1749.33     855    1772
#Mann= 7 ,-1 , 0
       0      .1       0  172.77     .12       0   477.7      .1       0
   525.6    .045       0  543.05      .1       0  575.64      .1       0
  673.58      .1       0
#XS Ineff= 2 , 0
                          655.69          1724.8
Permanent Ineff=
       F       F
Bank Sta=525.6,543.05
XS Rating Curve= 0 ,0
Exp/Cntr(USF)=0,0
Exp/Cntr=0.3,0.1

Type RM Length L Ch R = 1 ,4723    ,234.1,234.1,234.1
XS GIS Cut Line= 4
2496817.30201609625384.6352127122497009.57313201625745.634042619
2497117.48039095 625963.410510662497209.69204859626106.632872525
#Sta/Elev= 30
       0 1818.98    25.2 1808.75    58.9 1792.64  151.44  1760.4   197.9 1751.24
  265.961747.616  358.021743.744   381.2 1741.15   393.1 1738.19   404.9 1733.09
   423.8 1721.29   432.7 1717.32  460.811717.471   468.4 1716.89  484.731710.542
   494.4 1709.57  501.261710.541   513.1 1714.27   544.3 1715.28   562.2 1711.81
   575.6 1711.93  589.231714.045   607.8 1714.03   627.9 1721.09   637.7 1723.11
  665.951724.398   716.3 1728.94   746.6 1734.64  772.671741.616   822.4 1758.65
#Mann= 10 ,-1 , 0
       0      .1       0  151.44      .1       0  265.96      .1       0
  358.02      .1       0  460.81      .1       0  484.73    .045       0
  501.26      .1       0  589.23      .1       0  665.95     .05       0
  772.67      .1       0
#XS Ineff= 2 , 0
                          540.47         1716.38
Permanent Ineff=
       F       F
Bank Sta=484.73,501.26
XS Rating Curve= 0 ,0
Exp/Cntr(USF)=0,0
Exp/Cntr=0.3,0.1

Type RM Length L Ch R = 1 ,4489    ,291.1,291.1,291.1
XS GIS Cut Line= 4
2496679.96550471625465.075169376 2496811.4161656625777.025245219
2496848.69321869626024.2309656992496917.36147437626261.626935366
#Sta/Elev= 30
       0 1794.17    54.1 1772.45    84.4 1757.94    97.5 1753.23  187.721742.234
   327.5 1728.58   344.4  1724.5   372.8 1713.98  387.281710.008   409.2 1702.84
   429.4 1703.23   453.7 1701.72   465.8 1700.82  473.621701.771     486 1704.27
   506.3    1705   526.5 1704.19   534.6 1707.11   543.4    1712   550.8 1713.75
   558.8 1712.91     571 1708.16  582.35 1708.02  680.63 1707.29     737 1708.49
     757 1707.82  778.971716.363   791.2 1720.49   828.1 1724.88   835.6 1727.52
#Mann= 8 ,-1 , 0
       0      .1       0  187.72      .1       0  387.28      .1       0
   453.7    .045       0  473.62      .1       0  582.35     .02       0
  680.63    .035       0  778.97     .05       0
#XS Ineff= 2 , 0
                          503.43          1705.9
Permanent Ineff=
       F       F
Bank Sta=453.7,473.62
XS Rating Curve= 0 ,0
Exp/Cntr(USF)=0,0
Exp/Cntr=0.3,0.1

Type RM Length L Ch R = 1 ,4197    ,129.6,129.6,129.6
XS GIS Cut Line= 4
2496481.80853829625510.2000231142496538.70509301625702.471139043
2496619.14504967 625939.867108712496740.78595975626302.827888779
#Sta/Elev= 30
       0 1759.51    25.7 1754.75    62.5 1742.85    78.6 1738.89     105  1734.2
   159.2 1728.89   171.8 1730.05   234.7 1727.77   257.7 1725.75  268.261722.983
     277 1716.64   281.2  1710.6  288.021697.418   289.6 1694.36  293.441690.953
   298.1 1689.91  308.671690.958   331.9 1695.83  367.271697.163   416.3 1698.34
   445.9 1701.92  466.271702.697   509.2 1704.91  565.221705.551   677.9 1705.47
   702.9 1706.89  763.121706.932     775 1705.88   787.6 1708.86     834 1713.03
#Mann= 9 ,-1 , 0
       0      .1       0  268.26      .1       0  288.02      .1       0
  293.44    .045       0  308.67      .1       0  367.27      .1       0
  466.27     .05       0  565.22     .02       0  763.12     .05       0
Bank Sta=293.44,308.67
XS Rating Curve= 0 ,0
Exp/Cntr(USF)=0,0
Exp/Cntr=0.3,0.1

Type RM Length L Ch R = 1 ,4068    ,224.4,224.4,224.4
XS GIS Cut Line= 4
2496426.87393374 625561.21072734 2496428.8358839625790.758896357
2496528.89534219626004.611464073 2496685.8513552626391.115646093
#Sta/Elev= 30
       0 1740.26   28.721733.003    49.7 1729.71   101.7 1725.33   117.7 1722.95
   240.1 1720.53   247.4 1718.82   269.4 1707.45  314.071687.494   321.3  1686.6
  332.651687.494   348.9 1694.32   356.8  1696.3   388.7 1697.45   419.6 1696.36
   441.7 1703.53     494 1704.61  529.661703.597   545.6 1703.68   576.1 1705.84
   619.3 1705.87   662.4 1704.44   688.3 1706.08  730.081706.298   754.4 1706.23
     766 1704.53   770.3 1705.59  790.561706.601   809.2  1707.8   882.8 1715.97
#Mann= 7 ,-1 , 0
       0      .1       0   28.72      .1       0  314.07    .045       0
  332.65      .1       0  529.66     .02       0  730.08    .055       0
  790.56     .05       0
Bank Sta=314.07,332.65
XS Rating Curve= 0 ,0
Exp/Cntr(USF)=0,0
Exp/Cntr=0.3,0.1

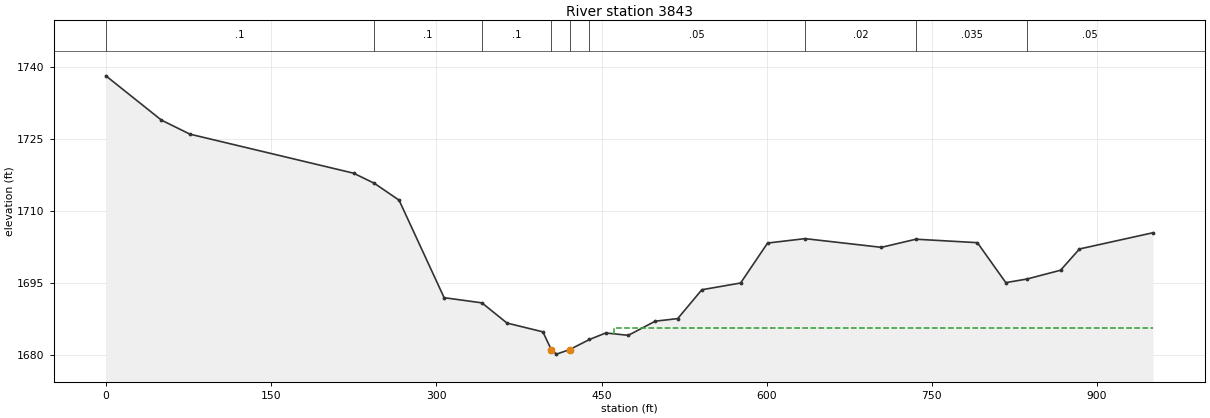
Type RM Length L Ch R = 1 ,3843    ,174.1,174.1,174.1
XS GIS Cut Line= 4
2496201.24966505 625576.906328642496269.91792074625847.655451071
2496336.62422626626181.1869787022496468.07488715626485.289253895
#Sta/Elev= 30
       0 1738.14    50.4 1728.93    76.3 1726.01   224.9 1717.89  243.681715.796
   266.2 1712.28   307.1    1692  341.431690.922   364.2 1686.72   396.8 1684.89
  404.38 1681.19   409.1 1680.26     4211681.192  439.051683.306   453.9 1684.66
   474.3 1684.17   498.8 1687.11   519.2 1687.65   541.1 1693.65   576.3 1695.05
   600.8 1703.36  634.78 1704.28   704.1 1702.47  735.551704.162   791.3 1703.44
   817.1 1695.13  836.321695.881   866.8 1697.71     884 1702.13   950.8 1705.51
#Mann= 9 ,-1 , 0
       0      .1       0  243.68      .1       0  341.43      .1       0
  404.38    .045       0     421      .1       0  439.05     .05       0
  634.78     .02       0  735.55    .035       0  836.32     .05       0
#XS Ineff= 2 , 0
                          460.91         1685.76
Permanent Ineff=
       F       F
Bank Sta=404.38,421
XS Rating Curve= 0 ,0
Exp/Cntr(USF)=0,0
Exp/Cntr=0.3,0.1