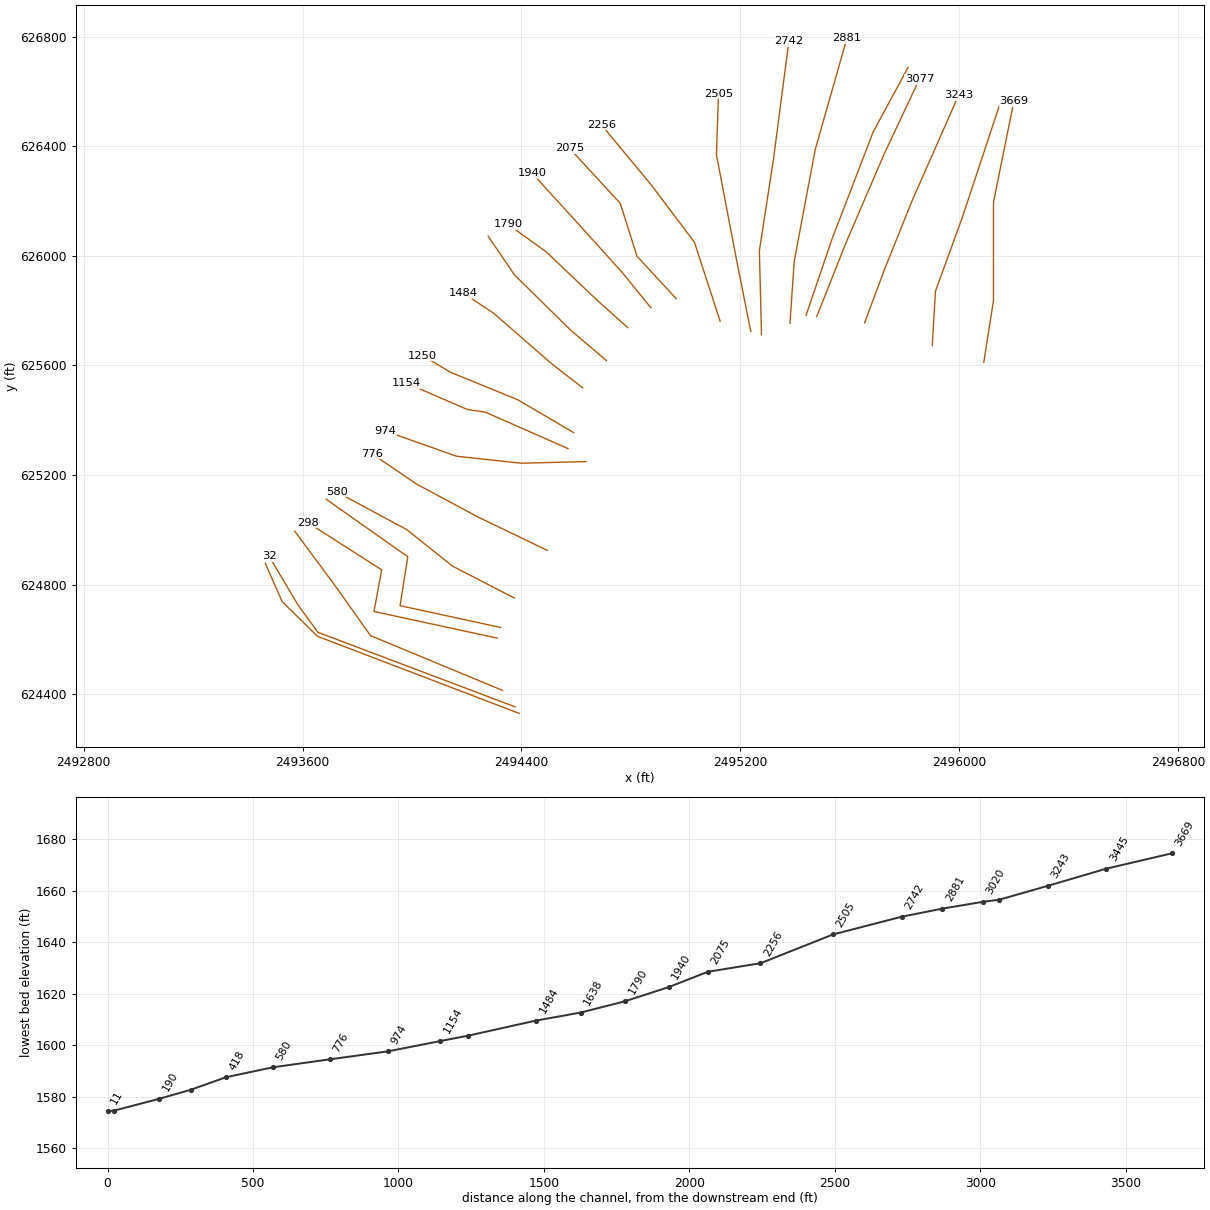
HEC-RAS study LROUGHRN.prj: LROUGHRN

--- LROUGHRN.g01 (geometry) --- (continued)

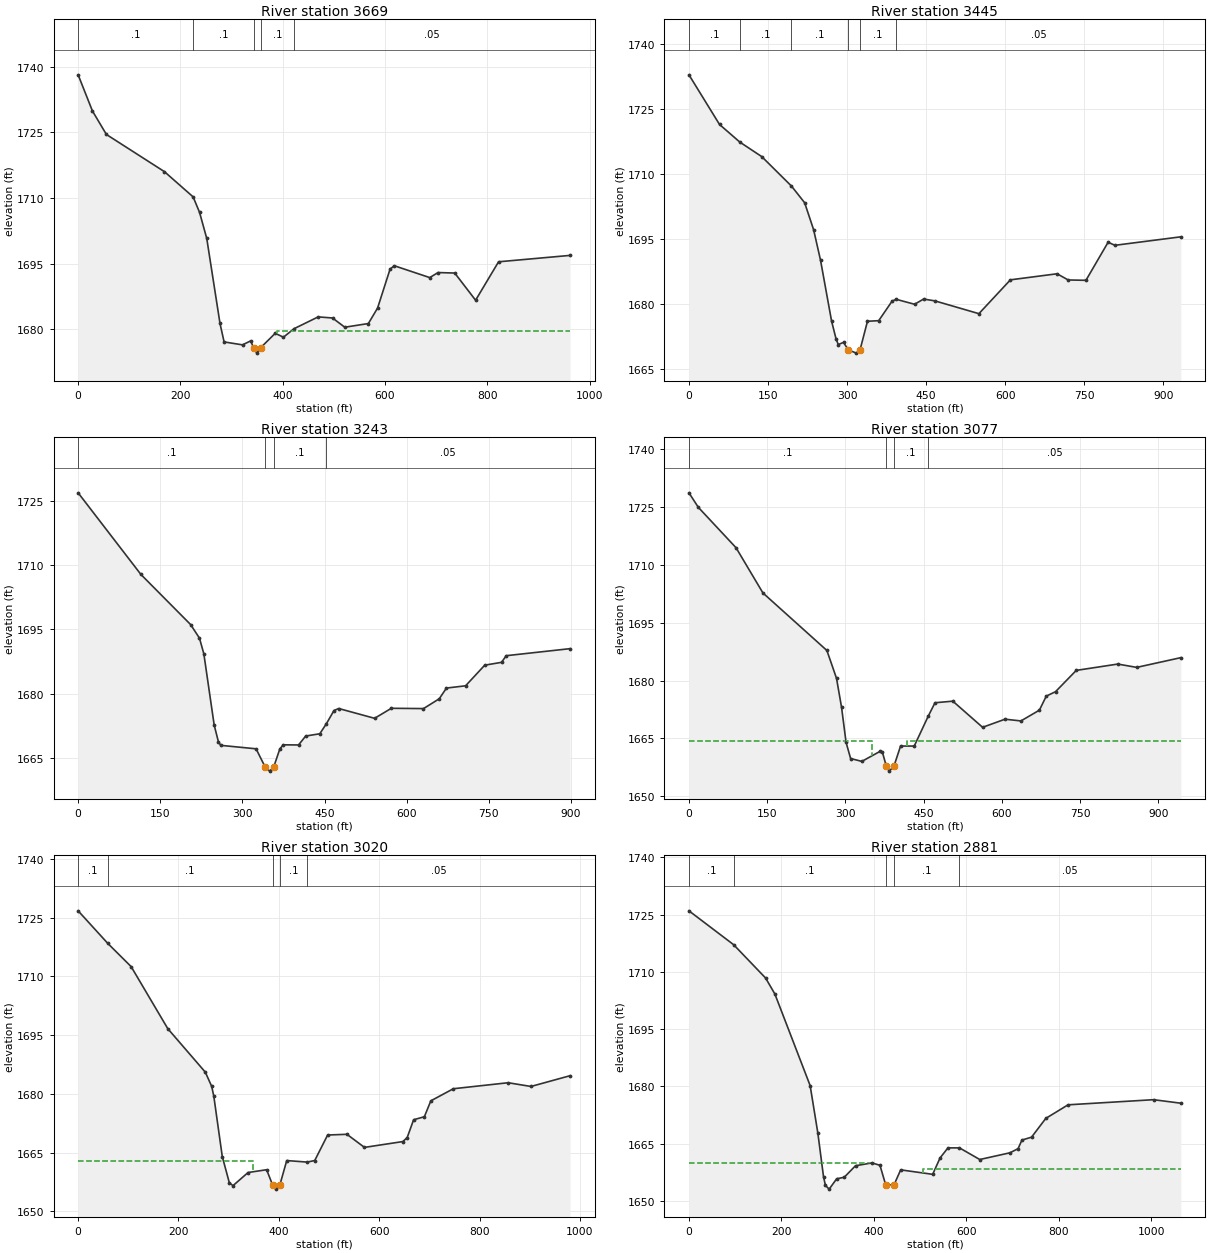
Type RM Length L Ch R = 1 ,3669    ,224.5,224.5,224.5
XS GIS Cut Line= 4
2496089.41850578625612.2214315662496124.73360871625835.883750095
2496124.73360871 626194.920629842496199.28771489626563.767260397
#Sta/Elev= 30
       0 1738.12      28 1729.85    55.3 1724.49   168.7    1716  224.85 1710.23
   237.4  1706.7   251.5 1700.73   277.4 1681.31   285.4 1677.09   321.4 1676.42
   337.4 1677.33  343.061675.766   349.4 1674.53  356.851675.767   385.4 1679.06
   401.4 1678.17  422.241680.115   469.4 1682.81   497.4 1682.56   521.4 1680.45
   567.5 1681.29   585.5 1684.82   609.9 1693.71   618.1  1694.5   687.5 1691.79
   703.8 1692.94   736.4 1692.83   777.2 1686.62   822.1  1695.4   961.8 1696.86
#Mann= 5 ,-1 , 0
       0      .1       0  224.85      .1       0  343.06    .045       0
  356.85      .1       0  422.24     .05       0
#XS Ineff= 2 , 0
                           388.2         1679.69
Permanent Ineff=
       F       F
Bank Sta=343.06,356.85
XS Rating Curve= 0 ,0
Exp/Cntr(USF)=0,0
Exp/Cntr=0.3,0.1

Type RM Length L Ch R = 1 ,3445    ,202,202,202
XS GIS Cut Line= 4
2495901.07129018625673.0418866052495912.84299116625871.198853021
2496010.94049928626139.9860252882496152.20091099626565.729210559
#Sta/Elev= 30
       0 1732.85      58 1721.39   96.551717.318   138.1 1713.97  194.521707.165
   219.5 1703.32   236.5  1697.1   249.7 1690.01   270.6 1675.99   279.1 1671.89
   283.3 1670.58   293.3 1671.08  302.011669.396   317.4  1668.6   324.71669.394
   338.7 1675.96     360 1676.09   385.5 1680.62  393.33 1681.02   428.1 1679.88
   445.1 1681.08   466.4 1680.67   550.1 1677.71   609.9 1685.52   698.4 1686.92
   719.5 1685.49   753.2 1685.41   795.3 1694.21     808 1693.49   933.2 1695.45
#Mann= 6 ,-1 , 0
       0      .1       0   96.55      .1       0  194.52      .1       0
  302.01    .045       0   324.7      .1       0  393.33     .05       0
Bank Sta=302.01,324.7
XS Rating Curve= 0 ,0
Exp/Cntr(USF)=0,0
Exp/Cntr=0.3,0.1

Type RM Length L Ch R = 1 ,3243    ,165.8,165.8,165.8
XS GIS Cut Line= 4
 2495653.8655697625755.4437934312495726.45772571625949.676859522
  2495826.517184626198.8445301652495997.20684814626585.348712184
#Sta/Elev= 30
       0 1726.86   114.7  1707.8   205.4 1696.11   221.6 1692.94   229.6 1689.28
   248.5 1672.64   256.1 1668.79   260.4 1667.91     325  1667.1  341.461662.885
     350 1661.89  357.281662.884   368.4 1667.07   374.6 1668.03   402.6    1668
   415.6 1670.08   441.4 1670.61  453.391672.948   467.3 1676.04   475.9 1676.51
   541.5 1674.22   572.1 1676.56   630.8 1676.49   659.6 1678.78   672.7 1681.28
   707.7 1681.81   742.6 1686.62   773.3 1687.29     782 1688.84   898.4 1690.48
#Mann= 4 ,-1 , 0
       0      .1       0  341.46    .045       0  357.28      .1       0
  453.39     .05       0
Bank Sta=341.46,357.28
XS Rating Curve= 0 ,0
Exp/Cntr(USF)=0,0
Exp/Cntr=0.5,0.3

Type RM Length L Ch R = 1 ,3077    ,56.5,56.5,56.5
XS GIS Cut Line= 4
2495479.25200523625778.9871953822495585.19731401626045.812417487
2495724.49577555626369.5341943052495853.98448628626644.207217061
#Sta/Elev= 30
       0 1728.62      18 1724.86    90.3  1714.4   141.9 1702.68   264.5 1687.79
     283 1680.56   292.6  1673.1   301.3 1663.98     310 1659.81   331.5 1659.06
   366.6 1661.67     371 1661.42  378.431657.848   384.1 1656.54  393.151657.849
   405.8 1663.04     432 1663.03  458.881670.784   471.8 1674.25     506 1674.66
   563.1 1667.89   606.1 1669.99   636.6 1669.54     672 1672.33   685.2 1675.97
   702.9 1677.11   742.7 1682.63   822.3 1684.27   858.6 1683.41   943.2 1685.93
#Mann= 4 ,-1 , 0
       0      .1       0  378.43    .045       0  393.15      .1       0
  458.88     .05       0
#XS Ineff= 2 , 0
          351.17 1664.32  418.38         1664.32
Permanent Ineff=
       F       F
Bank Sta=378.43,393.15
XS Rating Curve= 0 ,0
Exp/Cntr(USF)=0,0
Exp/Cntr=0.5,0.3

Type RM Length L Ch R = 1 ,3020    ,139.5,139.5,139.5
XS GIS Cut Line= 4
2495440.01300198625782.9110957072495534.18660979626059.546068624
 2495685.2567723626451.9361011322495812.78353287626687.370120636
#Sta/Elev= 30
       0 1726.72   59.171718.401   105.6 1712.49   178.7 1696.65   253.5 1685.55
   266.2 1681.92   270.4 1679.42   287.3 1664.02   301.4  1657.3   308.7 1656.59
   338.7 1659.94   375.7 1660.65   387.7 1656.73     394  1655.7  402.271656.861
   415.8 1662.99  456.561662.599   471.6    1663   497.3 1669.51   535.8 1669.69
   570.7 1666.35   647.3 1667.84   655.9 1668.87   668.7 1673.41   690.1 1674.17
     703 1678.23   747.9 1681.32   857.1 1682.85   902.6  1681.9   980.4 1684.64
#Mann= 5 ,-1 , 0
       0      .1       0   59.17      .1       0   387.7    .045       0
  402.27      .1       0  456.56     .05       0
#XS Ineff= 2 , 0
          348.42 1662.84
Permanent Ineff=
       F       F
Bank Sta=387.7,402.27
XS Rating Curve= 0 ,0
Exp/Cntr(USF)=0,0
Exp/Cntr=0.5,0.3

Type RM Length L Ch R = 1 ,2881    ,139.2,139.2,139.2
XS GIS Cut Line= 4
2495381.15449711625753.4818432692495396.85009841625981.068062123
2495473.36615475626387.1917457682495589.12121434626793.315429413
#Sta/Elev= 30
       0    1726   96.741717.114   165.8 1708.38   185.8 1704.21   262.1 1680.19
   278.8 1667.71     291 1656.32   295.1 1654.04   303.2 1653.06   319.5 1655.77
   335.8 1656.17   360.2 1659.19   395.7 1659.93   413.1 1659.31   425.4 1654.21
  443.141654.101   457.9 1658.11   527.1 1656.94     543 1661.23   560.1 1663.87
  585.071663.871   628.9 1660.82   694.1 1662.58   711.8 1663.67   720.1 1665.92
   740.9 1666.68   771.7  1671.6   819.9 1675.16  1004.8  1676.5  1063.7 1675.58
#Mann= 5 ,-1 , 0
       0      .1       0   96.74      .1       0   425.4    .045       0
  443.14      .1       0  585.07     .05       0
#XS Ineff= 2 , 0
          391.77 1659.89     507         1658.41
Permanent Ineff=
       F       F
Bank Sta=425.4,443.14
XS Rating Curve= 0 ,0
Exp/Cntr(USF)=0,0
Exp/Cntr=0.3,0.1

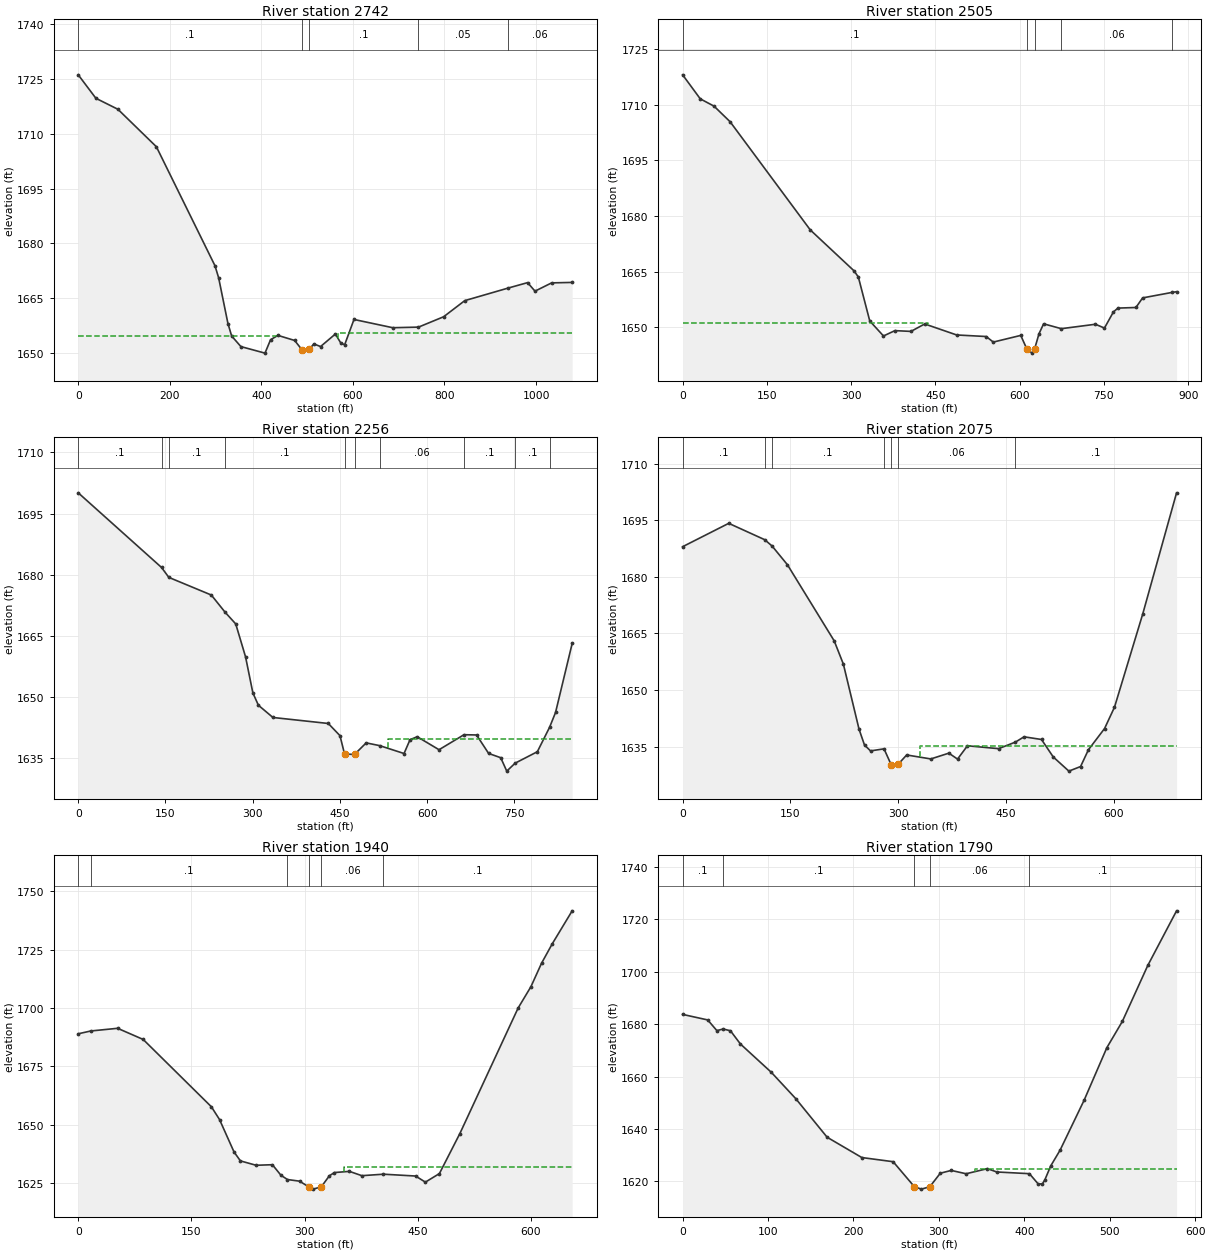
Type RM Length L Ch R = 1 ,2742    ,236.7,236.7,236.7
XS GIS Cut Line= 4
2495277.17113849625712.2808898552495269.32333784626018.345115211
2495320.33404207626347.9527425172495377.23059678626783.505678601
#Sta/Elev= 30
       0 1726.16    38.6 1719.73    86.6 1716.73   170.7 1706.46   298.7 1673.86
   306.7 1670.55     327 1658.03   335.1 1654.62   355.3 1651.72   407.9 1649.93
   420.1  1653.6   436.2 1654.79   472.7  1653.4   488.9 1650.82   504.2 1650.94
   514.7 1652.45   529.3 1651.73   561.7 1655.17   573.9 1652.61     582 1652.24
   602.3 1659.15     687 1656.89  743.221657.053   798.1 1659.89   844.3 1664.31
  938.341667.727   981.5 1669.24   997.7 1666.91    1034 1669.17  1078.9  1669.3
#Mann= 5 ,-1 , 0
       0      .1       0   488.9    .045       0   504.2      .1       0
  743.22     .05       0  938.34     .06       0
#XS Ineff= 2 , 0
          431.28 1654.58   567.9          1655.5
Permanent Ineff=
       F       F
Bank Sta=488.9,504.2
XS Rating Curve= 0 ,0
Exp/Cntr(USF)=0,0
Exp/Cntr=0.3,0.1

Type RM Length L Ch R = 1 ,2505    ,249.2,249.2,249.2
XS GIS Cut Line= 4
2495237.93213524625724.0525908312495179.07363037626020.307065374
2495112.36732484626369.5341943052495120.21512549626591.234562672
#Sta/Elev= 30
       0 1718.09    31.4 1711.61    55.9 1709.64    84.5 1705.44   227.2 1676.26
   304.9 1665.25   312.8 1663.57   333.2 1651.68   357.6 1647.64     378 1649.08
   406.5 1648.87     431 1650.88   487.9 1647.91   540.5 1647.49   553.1 1645.99
     602 1647.79  612.931644.094   622.3 1643.01  626.591644.093   634.5 1648.24
   642.7 1650.92  674.241649.605     735  1650.8     751 1649.77     767 1654.13
     775 1655.16     807 1655.32     819 1657.91  870.69 1659.37   879.4 1659.58
#Mann= 5 ,-1 , 0
       0      .1       0  612.93    .045       0  626.59      .1       0
  674.24     .06       0  870.69      .1       0
#XS Ineff= 2 , 0
          436.21 1651.22
Permanent Ineff=
       F       F
Bank Sta=612.93,626.59
XS Rating Curve= 0 ,0
Exp/Cntr(USF)=0,0
Exp/Cntr=0.3,0.1

Type RM Length L Ch R = 1 ,2256    ,180.7,180.7,180.7
XS GIS Cut Line= 4
2495126.10097598625761.3296439192495031.92736818626049.736317812
2494874.97135517626257.7030350412494692.50999006626477.441453245
#Sta/Elev= 30
       0  1700.1  143.28 1681.79  155.831679.357   228.9 1675.03  252.661670.804
   270.9 1667.94   287.8 1659.86   300.4 1651.01   309.9 1647.99   334.9 1644.99
   430.1 1643.52   450.2 1640.53   458.1 1636.01   475.2 1635.93   495.3 1638.76
  518.561638.082   560.4 1636.15   570.7 1639.54   583.1 1640.27   620.6 1637.08
  663.511640.763   685.1  1640.7   705.9 1636.17   726.7 1635.12   737.1 1631.83
  751.521633.787   789.7 1636.59  810.791642.601     821 1646.22   849.6 1663.15
#Mann= 10 ,-1 , 0
       0      .1       0  143.28      .1       0  155.83      .1       0
  252.66      .1       0   458.1    .045       0   475.2      .1       0
  518.56     .06       0  663.51      .1       0  751.52      .1       0
  810.79      .1       0
#XS Ineff= 2 , 0
                          533.61         1639.74
Permanent Ineff=
       F       F
Bank Sta=458.1,475.2
XS Rating Curve= 0 ,0
Exp/Cntr(USF)=0,0
Exp/Cntr=0.3,0.1

Type RM Length L Ch R = 1 ,2075    ,134.7,134.7,134.7
XS GIS Cut Line= 4
2494965.22106265625843.7315507452494821.99870079625998.725613586
2494761.17824575626190.9967295152494574.79298031626393.077596256
#Sta/Elev= 30
       0 1687.97    64.2 1694.16  114.251689.826  124.561688.144   145.9 1683.19
     211 1663.03   223.8 1656.85   245.6 1639.62   253.2 1635.42   261.6 1633.88
  280.371634.423   290.3 1630.22   299.8 1630.29   311.9  1632.8   345.5 1631.75
   370.6 1633.28   382.7 1631.71   396.5 1635.23   439.8 1634.47  463.191636.203
   475.3 1637.61   499.6  1636.9   515.9 1632.28   537.7 1628.52     554 1629.74
   564.9 1634.18   587.4 1639.81   601.2 1645.46   640.5 1670.14   687.6 1702.24
#Mann= 7 ,-1 , 0
       0      .1       0  114.25      .1       0  124.56      .1       0
  280.37     .06       0   290.3    .045       0   299.8     .06       0
  463.19      .1       0
#XS Ineff= 2 , 0
                          330.32         1635.11
Permanent Ineff=
       F       F
Bank Sta=290.3,299.8
XS Rating Curve= 0 ,0
Exp/Cntr(USF)=0,0
Exp/Cntr=0.3,0.1

Type RM Length L Ch R = 1 ,1940    ,150.8,150.8,150.8
XS GIS Cut Line= 4
2494873.00940501625810.3783979822494770.98799656625935.943208385
2494606.18418291626118.4045735012494439.41841909626300.865938617
#Sta/Elev= 30
       0 1688.98   16.611690.183    52.2 1691.33    86.1 1686.56   176.5 1657.78
   187.3 1652.32   206.5 1638.47     215 1634.63   235.8 1632.76   257.4    1633
   268.8 1628.46  277.411626.663   293.4 1625.96  305.591623.524   311.3 1622.56
  322.191623.524   332.9 1628.26   339.6 1629.65   359.5 1630.15     376 1628.31
  404.671628.942   447.2 1628.16   460.2 1625.55   478.8 1629.21   505.9 1646.31
   583.1 1699.97   600.1 1709.11   614.2 1719.15   628.4 1727.46   654.8 1741.56
#Mann= 6 ,-1 , 0
       0      .1       0   16.61      .1       0  277.41     .06       0
  305.59    .045       0  322.19     .06       0  404.67      .1       0
#XS Ineff= 2 , 0
                           352.4         1631.88
Permanent Ineff=
       F       F
Bank Sta=305.59,322.19
XS Rating Curve= 0 ,0
Exp/Cntr(USF)=0,0
Exp/Cntr=0.3,0.1

Type RM Length L Ch R = 1 ,1790    ,151.9,151.9,151.9
XS GIS Cut Line= 4
2494788.64554802625737.7862419692494678.77633892625835.883750095
2494490.42912332626014.4212148862494351.13066178626114.480673176
#Sta/Elev= 30
       0 1683.75    29.4 1681.63    40.1 1677.56   47.531678.172      56  1677.5
    67.7 1672.44   103.8 1661.65   132.4  1651.6   169.2 1636.84   209.8 1629.09
   246.5  1627.5  271.331617.949   279.6 1617.03  289.421617.948   301.7 1623.11
   314.5 1624.17   331.9  1622.9   356.8 1624.85   367.8 1623.58  406.041622.928
   416.3 1619.01   421.3 1619.04   424.1 1620.58     431 1625.91   441.9 1631.89
     470 1650.93   496.7 1671.05   514.8 1681.06   544.7  1702.5   578.3  1723.3
#Mann= 5 ,-1 , 0
       0      .1       0   47.53      .1       0  271.33    .045       0
  289.42     .06       0  406.04      .1       0
#XS Ineff= 2 , 0
                          342.39          1624.8
Permanent Ineff=
       F       F
Bank Sta=271.33,289.42
XS Rating Curve= 0 ,0
Exp/Cntr(USF)=0,0
Exp/Cntr=0.3,0.1

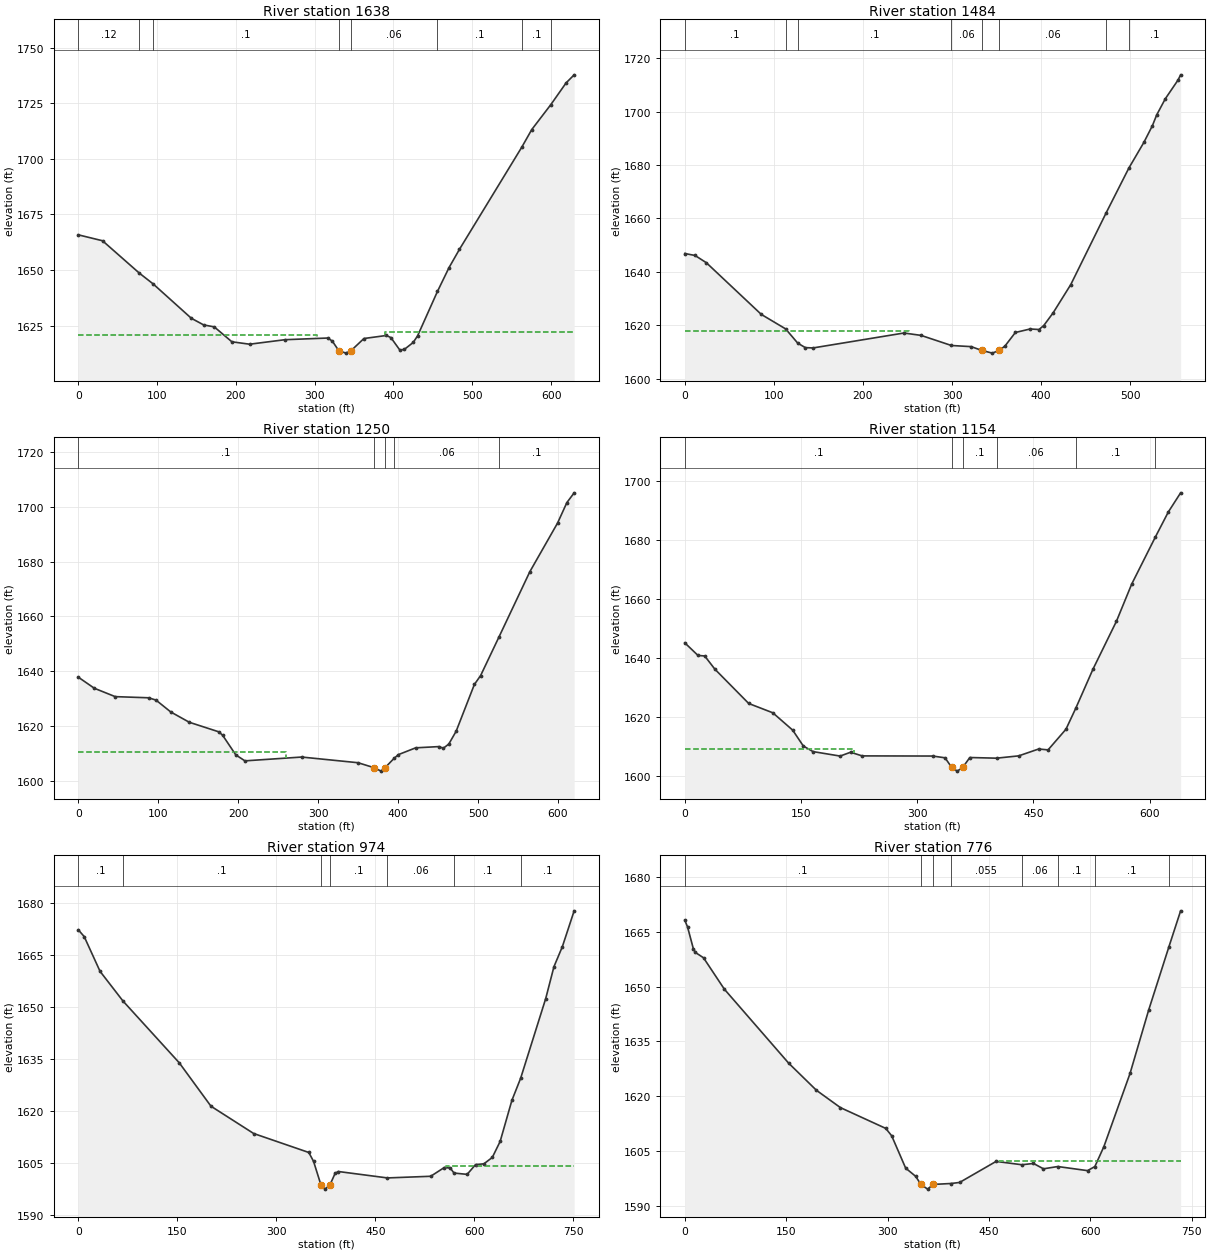
Type RM Length L Ch R = 1 ,1638    ,153.3,153.3,153.3
XS GIS Cut Line= 4
2494710.16754152625618.1072820542494580.67883079625727.976491156
2494374.67406373625930.0573578972494278.53850576  626071.3177696
#Sta/Elev= 30
       0 1665.82    30.7 1663.16   77.541648.578   94.671643.849   143.4 1628.33
   159.1 1625.33   172.5 1624.46   194.9 1617.75   217.4 1616.67   262.2 1618.69
   316.8 1619.45   322.5    1618  330.461613.808   339.6 1612.66  346.23 1613.81
   362.5 1619.23     391 1620.59   396.7 1619.64     408 1614.07   413.7 1614.32
     425 1617.45   430.6 1620.44  455.841640.418   470.5  1651.1   483.6 1659.24
  562.85 1705.23   575.5 1713.14  599.78 1724.38   619.1 1734.12   629.3 1737.73
#Mann= 8 ,-1 , 0
       0     .12       0   77.54      .1       0   94.67      .1       0
  330.46    .045       0  346.23     .06       0  455.84      .1       0
  562.85      .1       0  599.78      .1       0
#XS Ineff= 2 , 0
          303.43 1620.66  388.89         1621.96
Permanent Ineff=
       F       F
Bank Sta=330.46,346.23
XS Rating Curve= 0 ,0
Exp/Cntr(USF)=0,0
Exp/Cntr=0.3,0.1

Type RM Length L Ch R = 1 ,1484    ,234.6,234.6,234.6
XS GIS Cut Line= 4
2494623.84173437625518.0478237642494508.08667478625608.297531241
2494298.15800739625790.7588963572494188.28879829625863.351052371
#Sta/Elev= 30
       0 1646.84    11.5 1646.11    24.2 1643.39    85.9 1624.04  113.211618.617
  126.791613.284   135.3 1611.61   143.9 1611.49     246 1617.08   265.2 1616.19
  299.281612.409   321.5 1611.98  333.191610.587   345.2 1609.55  352.991610.589
   359.4  1612.2   371.1 1617.28   387.7 1618.59   397.6 1618.39   402.9 1619.85
   413.5 1624.64   433.3 1635.22  473.171662.176  498.451678.802   515.3 1688.41
   524.9 1694.68   529.7 1698.69   539.3 1704.71   553.7 1711.78   556.6 1713.73
#Mann= 8 ,-1 , 0
       0      .1       0  113.21      .1       0  126.79      .1       0
  299.28     .06       0  333.19    .045       0  352.99     .06       0
  473.17      .1       0  498.45      .1       0
#XS Ineff= 2 , 0
          251.85 1617.71
Permanent Ineff=
       F       F
Bank Sta=333.19,352.99
XS Rating Curve= 0 ,0
Exp/Cntr(USF)=0,0
Exp/Cntr=0.3,0.1

Type RM Length L Ch R = 1 ,1250    ,95.5,95.5,95.5
XS GIS Cut Line= 4
2494590.48858161625355.205960274 2494386.4457647625474.884920189
2494141.20199438625574.9443784782494039.18058593625635.764833517
#Sta/Elev= 30
       0 1637.87      20 1633.84    46.1 1630.79    87.8 1630.37    97.1 1629.54
   115.6 1625.21   138.8 1621.45   175.9 1617.95   180.6 1616.67     197 1609.55
   208.4 1607.39   279.4 1608.78   349.9 1606.71  369.581604.931   378.8 1603.65
  383.731604.929  394.941608.297   400.4 1609.67     422 1612.14   451.1 1612.59
   456.6    1612   463.4 1613.52   472.6 1618.19   495.4 1635.23   503.2 1638.47
  526.061652.464   564.8 1676.32   599.5 1694.06   611.1 1701.49   620.2 1705.04
#Mann= 5 ,-1 , 0
       0      .1       0  369.58    .045       0  383.73      .1       0
  394.94     .06       0  526.06      .1       0
#XS Ineff= 2 , 0
          260.22 1610.63
Permanent Ineff=
       F       F
Bank Sta=369.58,383.73
XS Rating Curve= 0 ,0
Exp/Cntr(USF)=0,0
Exp/Cntr=0.3,0.1

Type RM Length L Ch R = 1 ,1154    ,179.9,179.9,179.9
XS GIS Cut Line= 4
2494570.29507774625296.775928647 2494267.9403134 625429.67912176
2494201.48871685625439.6468612442493978.87586838625536.001676251
#Sta/Elev= 30
       0  1645.1      17 1640.83    25.7 1640.64    38.8 1636.17    82.5 1624.52
   113.6 1621.36   139.3 1615.46     153 1610.08   165.5 1608.19   200.5 1606.67
     214 1607.97   228.9 1606.73     320 1606.68   335.9 1606.08  344.561602.809
   351.7 1601.56  358.74 1602.81   367.9 1606.18  402.381605.955     431 1606.74
   456.8 1609.07   468.9 1608.77     492 1615.78  504.821622.996   526.9 1636.18
   557.2 1652.45   576.8 1665.01  607.27 1680.95   624.1  1689.5     640 1696.01
#Mann= 6 ,-1 , 0
       0      .1       0  344.56    .045       0  358.74      .1       0
  402.38     .06       0  504.82      .1       0  607.27      .1       0
#XS Ineff= 2 , 0
          217.97 1609.04
Permanent Ineff=
       F       F
Bank Sta=344.56,358.74
XS Rating Curve= 0 ,0
Exp/Cntr(USF)=0,0
Exp/Cntr=0.3,0.1

Type RM Length L Ch R = 1 ,974     ,198.2,198.2,198.2
XS GIS Cut Line= 4
2494635.61343534625249.2606514972494398.21746568625243.374801009
2494162.78344617625268.8801531222493901.84407456625361.091810761
#Sta/Elev= 30
       0 1672.22     8.9 1670.27    32.9 1660.27   67.661651.718   152.9 1633.93
   200.9 1621.44   265.6 1613.58   349.1 1608.12   356.3 1605.55   367.51598.765
   373.7 1597.57  381.021598.764     389 1602.13   393.9 1602.64  468.151600.794
   533.7 1601.27   554.3 1603.79   563.4 1603.63  568.991602.197   588.9 1601.82
   601.6 1604.61   614.3 1604.86     627 1606.69   638.9  1611.3   656.7 1623.13
  669.921629.476   707.9 1652.42   720.4 1661.61   733.1 1667.36     751 1677.69
#Mann= 7 ,-1 , 0
       0      .1       0   67.66      .1       0   367.5    .045       0
  381.02      .1       0  468.15     .06       0  568.99      .1       0
  669.92      .1       0
#XS Ineff= 2 , 0
                          557.48         1604.17
Permanent Ineff=
       F       F
Bank Sta=367.5,381.02
XS Rating Curve= 0 ,0
Exp/Cntr(USF)=0,0
Exp/Cntr=0.3,0.1

Type RM Length L Ch R = 1 ,776     ,196.7,196.7,196.7
XS GIS Cut Line= 4
2494494.35302364624925.5388746782494241.26145267625047.179784755
2494017.59913414 625166.858744672493852.79532049625278.689903935
#Sta/Elev= 30
       0 1668.22       4 1666.43    12.7 1660.38    15.7 1659.39    27.7 1657.93
    58.5 1649.33   153.6 1629.05   194.8 1621.59   230.3 1616.84   297.3 1611.15
   306.1 1609.12   326.8 1600.25   341.6    1598  349.351595.779   359.3 1594.49
  367.451595.781  393.751596.032   406.6 1596.32   460.6 1602.09  498.751601.177
   515.9 1601.53   530.7 1600.06   551.91600.686   595.9 1599.56  606.741600.682
   620.1 1606.15   658.8 1626.22   686.3 1643.56  716.281660.932733.6391 1670.81
#Mann= 8 ,-1 , 0
       0      .1       0  349.35    .045       0  367.45      .1       0
  393.75    .055       0  498.75     .06       0   551.9      .1       0
  606.74      .1       0  716.28      .1       0
#XS Ineff= 2 , 0
                           464.2         1602.32
Permanent Ineff=
       F       F
Bank Sta=349.35,367.45
XS Rating Curve= 0 ,0
Exp/Cntr(USF)=0,0
Exp/Cntr=0.3,0.1

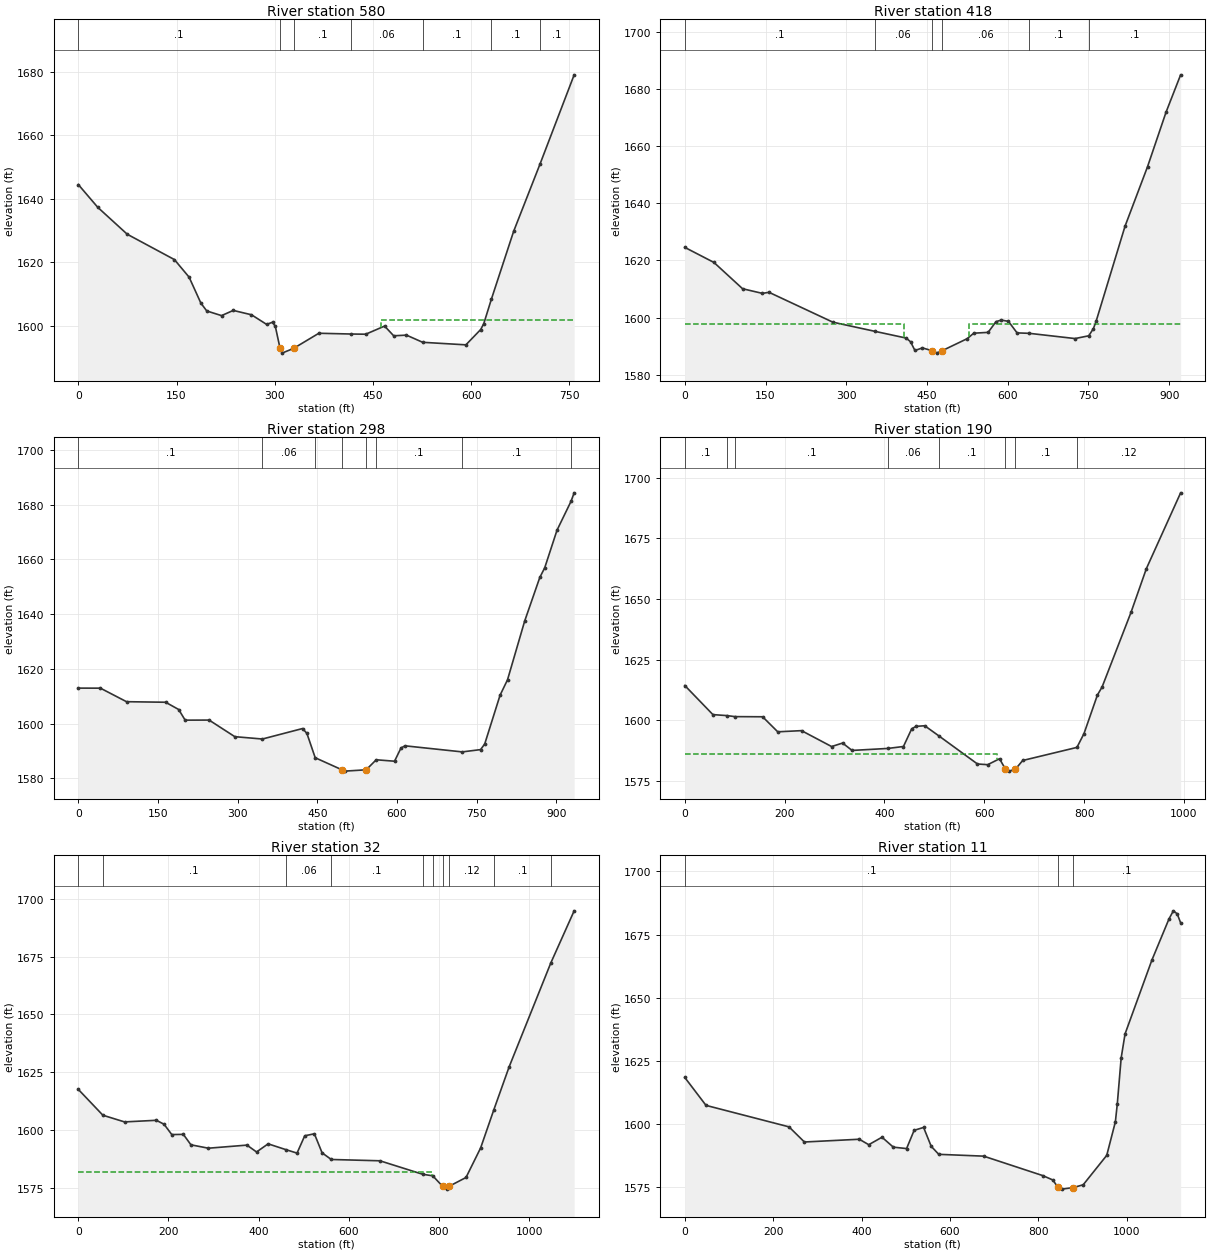
Type RM Length L Ch R = 1 ,580     ,161.2,161.2,161.2
XS GIS Cut Line= 4
2494373.16451936624751.9743749222494147.14786063624868.514214577
2493981.16687688625000.9458505482493725.13238067625138.674751958
#Sta/Elev= 30
       0 1644.47    29.7  1637.3    74.7 1628.83   146.7 1620.85   169.2 1615.31
   187.2 1607.13   196.2 1604.66   218.7  1603.2   236.7 1604.83   264.5 1603.46
   287.6 1600.43   296.6 1601.11   300.9  1599.8  308.16 1592.86   311.1 1591.38
  328.69 1592.86   367.4 1597.64  417.061597.396     439 1597.34   467.8  1599.9
   481.7 1596.84   501.2 1597.05  526.01 1594.79     592 1593.99   614.6 1598.82
   619.3 1600.67  631.091608.479   664.9 1629.73  705.251650.955757.3605 1679.04
#Mann= 7 ,-1 , 0
       0      .1       0  308.16    .045       0  328.69      .1       0
  417.06     .06       0  526.01      .1       0  631.09      .1       0
  705.25      .1       0
#XS Ineff= 2 , 0
                             462         1601.77
Permanent Ineff=
       F       F
Bank Sta=308.16,328.69
XS Rating Curve= 0 ,0
Exp/Cntr(USF)=0,0
Exp/Cntr=0.5,0.3

Type RM Length L Ch R = 1 ,418     ,120.5,120.5,120.5
XS GIS Cut Line= 4
2494323.72337526624644.2633109992493956.44630483624723.722292581
2493984.69838717624902.0635623562493686.28576745625112.188424764
#Sta/Elev= 30
       0  1624.6    54.2 1619.31   107.4 1610.09   144.1 1608.47   156.5 1608.84
   275.2 1598.36  352.511595.184   411.4 1592.79   419.5 1591.48   427.6 1588.44
   441.6 1589.34  458.531588.413   468.1 1587.51  478.741588.413   524.8 1592.59
   536.9  1594.5   563.6 1594.79   578.3 1598.55   588.1 1599.11   601.4 1598.65
   617.4 1594.61  640.22 1594.45   725.1 1592.62  750.661593.593   759.3 1596.14
   764.2 1598.63     818 1632.02   859.8 1652.88   894.2 1672.01921.3085 1685.12
#Mann= 6 ,-1 , 0
       0      .1       0  352.51     .06       0  458.53    .045       0
  478.74     .06       0  640.22      .1       0  750.66      .1       0
#XS Ineff= 2 , 0
             408 1597.64     528         1597.64
Permanent Ineff=
       F       F
Bank Sta=458.53,478.74
XS Rating Curve= 0 ,0
Exp/Cntr(USF)=0,0
Exp/Cntr=0.5,0.3

Type RM Length L Ch R = 1 ,298     ,108.3,108.3,108.3
XS GIS Cut Line= 4
2494311.36308924 624605.416697782493861.09552693624702.533230826
2493889.34760928624854.3881734062493620.95282704625025.666422596
#Sta/Elev= 30
       0 1612.97    41.6 1612.95    90.7 1608.01   164.3 1607.81   188.9 1605.16
   201.1 1601.27   246.2  1601.3   294.6 1595.24   346.51594.383   422.1 1598.21
   430.3 1596.45  445.951587.548  496.361583.142   501.7 1582.66  541.881583.142
  560.831586.804   595.3 1586.28   607.5 1591.12   615.1  1591.9  722.741589.682
   757.3 1590.52   765.1 1592.58     794 1610.39     808    1616   840.4 1637.51
   868.8 1653.38     878 1656.87   901.2 1670.63  927.521681.149933.4722 1684.27
#Mann= 8 ,-1 , 0
       0      .1       0   346.5     .06       0  445.95      .1       0
  496.36    .045       0  541.88      .1       0  560.83      .1       0
  722.74      .1       0  927.52     .12       0
Bank Sta=496.36,541.88
XS Rating Curve= 0 ,0
Exp/Cntr(USF)=0,0
Exp/Cntr=0.5,0.3

Type RM Length L Ch R = 1 ,190     ,157.2,157.2,157.2
XS GIS Cut Line= 4
2494330.78639585624414.7151419822493848.73524091624614.245473512
2493718.06936009624797.8840087252493571.51168294624995.648585109
#Sta/Elev= 30
       0  1614.4    56.3 1602.42    84.31602.018  100.471601.591   155.9 1601.53
   186.2 1595.34   233.8 1595.82   294.1 1589.27   316.1 1590.71   335.1 1587.67
   406.6 1588.49     438 1589.29   454.6  1596.6   463.3 1597.58   480.6 1597.84
  508.641593.708   586.3 1582.09   606.8  1581.8   630.5 1584.25  642.371579.929
   649.8 1579.15  662.171579.927   676.9 1583.53  785.541588.921   799.7 1594.61
   826.6  1610.5     836 1613.83   893.8 1644.49   924.6 1662.52993.2457 1693.74
#Mann= 8 ,-1 , 0
       0      .1       0    84.3      .1       0  100.47      .1       0
   406.6     .06       0  508.64      .1       0  642.37    .045       0
  662.17      .1       0  785.54     .12       0
#XS Ineff= 2 , 0
          625.51 1586.09
Permanent Ineff=
       F       F
Bank Sta=642.37,662.17
XS Rating Curve= 0 ,0
Exp/Cntr(USF)=0,0
Exp/Cntr=0.3,0.1

Type RM Length L Ch R = 1 ,32      ,20.9,20.9,20.9
XS GIS Cut Line= 4
2494376.69602965624354.6794670082493656.26792997624626.605759536
2493583.87196897624725.4880477282493477.92666019624903.829317502
#Sta/Elev= 30
       0 1617.61   54.481606.448   102.5 1603.56   173.1 1604.26   190.2 1602.55
   207.3 1598.09     233 1598.17   249.8 1593.66   288.5 1592.19   374.1 1593.53
   395.4 1590.56   421.1 1594.08  459.841591.612   485.2 1590.07   502.3 1597.56
   523.7 1598.43   540.8 1590.19  561.181587.317   669.1 1586.75  763.861580.933
  786.381580.246  808.121575.719   817.1  1574.5  822.511575.719   860.1 1579.53
   892.6 1592.34  921.741608.759   955.7 1627.33 1048.211672.2791100.028 1694.82
#Mann= 10 ,-1 , 0
       0      .1       0   54.48      .1       0  459.84     .06       0
  561.18      .1       0  763.86     .06       0  786.38     .12       0
  808.12    .045       0  822.51     .12       0  921.74      .1       0
 1048.21     .12       0
#XS Ineff= 2 , 0
          783.54 1581.96
Permanent Ineff=
       F       F
Bank Sta=808.12,822.51
XS Rating Curve= 0 ,0
Exp/Cntr(USF)=0,0
Exp/Cntr=0.3,0.1

Type RM Length L Ch R = 1 ,11      ,11,11,11
XS GIS Cut Line= 4
2494391.57662102 624330.833924912493655.02601292624611.925687593
2493525.75386537624738.1915061242493464.12412062624877.985805212
#Sta/Elev= 30
       0 1618.48      48 1607.44   235.8 1598.94   270.6 1592.95   394.8 1594.04
   416.2 1591.88   446.2 1594.84   471.8 1590.91   501.8 1590.35   518.9 1597.57
   540.3 1598.71   557.5 1591.25   574.6 1588.07   676.2 1587.35   809.8 1579.66
   832.7 1577.92   844.1 1575.06   852.9  1574.3   878.2 1574.88   901.4 1576.02
   954.7 1587.67   974.2 1600.92   978.6 1608.07   987.3 1626.18   996.1 1635.72
  1056.8 1664.92  1095.5 1681.22  1105.4 1684.43  1114.1 1683.241121.847 1679.69
#Mann= 3 , 0 , 0
       0      .1       0   844.1    .045       0   878.2      .1       0
Bank Sta=844.1,878.2
XS Rating Curve= 0 ,0
Exp/Cntr(USF)=0,0
Exp/Cntr=0.3,0.1
LCMann Table=0

Chan Stop Cuts=-1
Use User Specified Reach Order=0
Composite Channel Slope=5